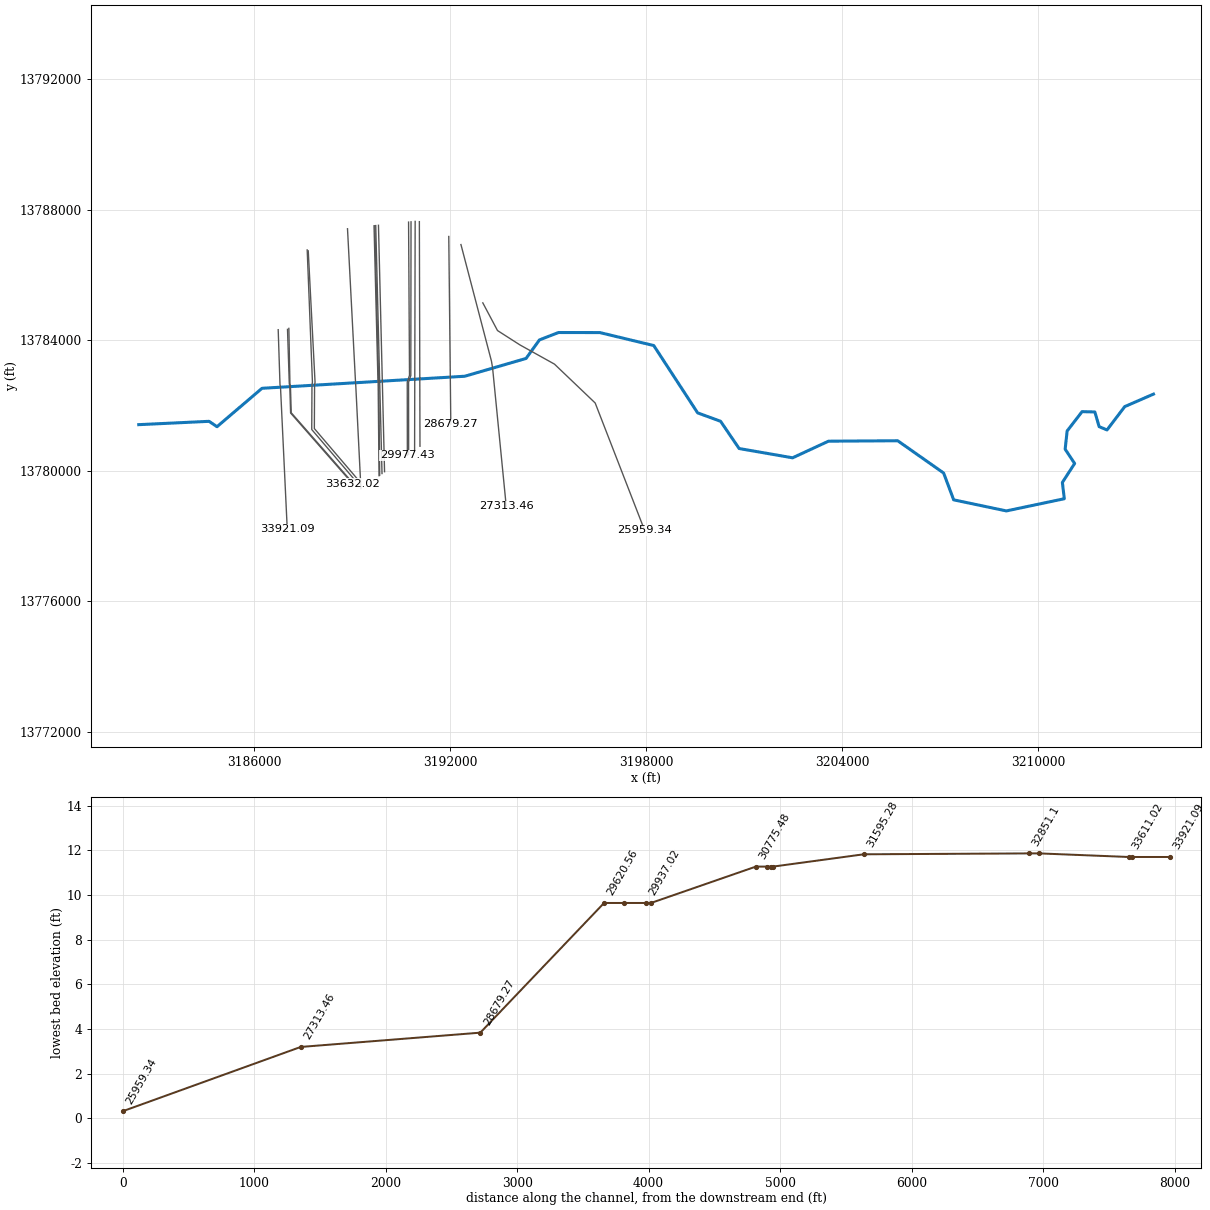
--- B104_00_00.prj (project) ---

Proj Title=B104-00-00
Current Plan=p02
Default Exp/Contr=.3,.1
English Units
Geom File=g01
Geom File=g02
Flow File=f02
Flow File=f03
Plan File=p02
Plan File=p03
Y Axis Title=Elevation
X Axis Title(PF)=Main Channel Distance
X Axis Title(XS)=Station
BEGIN DESCRIPTION:
Armand Bayou
Horsepen Bayou
HCFCD Unit B104-00-00
Flood Hazard Model
10, 2, 1, 0.2% Event
Filename B104_00_00.prj
Prepared by: Christopher Moss Date: 6/15/2004
Reviewd by:		Date:
Status FINAL
END DESCRIPTION:
DSS Export Rating Curves= 0
DSS Export Rating Curve Sorted= 0
DSS Export Volume Flow Curves= 0
DXF OffsetX= 0
DXF OffsetY= 0
DXF ScaleX= 1
DXF ScaleY= 10

--- B104_00_00.p02 (plan) ---

Plan Title=FEMA Effective June 2007
Version=Version 3.0.1  Mar 2001
Short Identifier=FEMAeff0607
Geom File=g01
Flow File=f02
Subcritical Flow
K Sum by GR= 0
Std Step Tol= 0.01
Critical Tol= 0.01
Num of Std Step Trials= 20
Max Error Tol= 0.3
Flow Tol Ratio= 0.001
Split Flow NTrial= 30
Split Flow Tol= 0.02
Split Flow Ratio= 0.02
Log Output Level= 0
Friction Slope Method= 0
Unsteady Friction Slope Method= 2
Secant Critical Depth
Global Vel Dist= 0 , 0 , 0
Global Log Level= 0
CheckData=True
Encroach Param=-1 ,0,0, 2
Computation Interval=1HOUR
Output Interval=1HOUR
Run HTab= 0
Run UNet= 0
Run PostProcess= 0
UNET Theta= 1
UNET ZTol= 0.02
UNET ZSATol= 0.1
UNET MxIter= 20
UNET MaxInSteps= 20
UNET DtIC= 0
UNET DtMin= 0
UNET MaxCRTS= 20
UNET WFStab= 2
UNET SFStab= 1
UNET WFX= 1
UNET SFX= 1
UNET Convert EG Bridges=-1
UNET Use Existing IB Tables=-1
Instantaneous Interval=1HOUR
Write IC File= 0
IC Time=0
Write Velocity= 0
Write Detailed= 0

--- B104_00_00.p03 (plan) ---

Plan Title=Floodway
Version=Version 3.0.1  Mar 2001
Short Identifier=Floodway0607
Geom File=g02
Flow File=f03
Subcritical Flow
K Sum by GR= 0
Std Step Tol= 0.01
Critical Tol= 0.01
Num of Std Step Trials= 20
Max Error Tol= 0.3
Flow Tol Ratio= 0.001
Split Flow NTrial= 30
Split Flow Tol= 0.02
Split Flow Ratio= 0.02
Log Output Level= 0
Friction Slope Method= 0
Unsteady Friction Slope Method= 2
Secant Critical Depth
Global Vel Dist= 0 , 0 , 0
Global Log Level= 0
CheckData=True
Encroach Param=-1 ,0,0, 2
Encroach River=B104-00-00
Encroach Reach=MAIN
Encroach Node=33921.09
       1 1724.93 1810.55
Encroach Node=33632.02
       1 4956.89 5047.47
Encroach Node=33611.02
       1 4956.89 5043.11
Encroach Node=33271.4
       1    4877    5123
Encroach Node=32931.84
       1    4877    5123
Encroach Node=32851.1
       1 4947.99 5052.01
Encroach Node=31595.28
       1 4908.14    5073
Encroach Node=30906.64
       1 4894.07 5055.36
Encroach Node=30886.64
       1 4894.07 5055.36
Encroach Node=30856.34
       1 4880.07 5055.36
Encroach Node=30775.48
       1 4894.07 5055.36
Encroach Node=29977.43
       1  4837.5 5167.74
Encroach Node=29937.02
       1 4877.18 5177.79
Encroach Node=29774.81
       1 4934.07  5171.1
Encroach Node=29620.56
       1 4888.28 5133.84
Encroach Node=28679.27
       1  4883.9 5118.44
Encroach Node=27313.46
       1 4819.32 5267.08
Encroach Node=25959.34
       1 4881.36 5162.94
Encroach Node=25919.28
       1 4899.63 5146.13
Encroach Node=25823.8
       1 4878.27 5146.13
Encroach Node=25728.31
       1 4878.27 5111.64
Encroach Node=25536.03
       1 4868.95  5130.5
Encroach Node=24058.15
       1 4892.12    5118
Encroach Node=24038.15
       1 4894.46 5105.25
Encroach Node=23905.5
       1 4889.93 5106.69
Encroach Node=23772.84
       1 4889.93 5106.69
Encroach Node=23692.71
       1 4869.45    5096
Encroach Node=22758.24
       1    4931 5150.56
Encroach Node=21821.68
       1 4911.22 5088.78
Encroach Node=21072.13
       1  4910.1    5126
Encroach Node=21031.83
       1  4910.1  5089.9
Encroach Node=20942.9
       1 4864.69    5141
Encroach Node=20853.92
       1 4864.69    5140
Encroach Node=20693.87
       1 4838.28 5214.05
Encroach Node=19846.57
       1  4850.5 5079.23
Encroach Node=19812.71
       1 4831.53  5138.3
Encroach Node=19737.92
       1 4831.53    5220
Encroach Node=19663.12
       1 4899.18 5148.39
Encroach Node=19580.65
       1 4760.04 5138.28
Encroach Node=19232.53
       1 4855.49 5083.37
Encroach Node=19212.44
       1  4834.9 5083.37
Encroach Node=19151.64
       1  4834.9 5103.37
Encroach Node=19090.84
       1 4900.01 5103.37
Encroach Node=19010.58
       1 4896.54    5089
Encroach Node=17730.46
       1 4932.26 5107.74
Encroach Node=16521.13
       1 4912.26 5087.74
Encroach Node=16480.97
       1 4912.26    5143
Encroach Node=16422.9
       1 4912.26    5143
Encroach Node=16364.84
       1 4912.26    5143
Encroach Node=16204.84
       1    4888    5141
Encroach Node=14932.88
       1 4902.75 5097.25
Encroach Node=13216.11
       1 4880.46 5106.61
Encroach Node=11490.4
       1 4920.32 5079.68
Encroach Node=11450.35
       1 4920.32 5079.68
Encroach Node=11295.96
       1 4920.32 5079.68
Encroach Node=11141.62
       1    4900 5089.68
Encroach Node=10978.64
       1    4911    5200
Encroach Node=9906.905
       1    4900    5200
Encroach Node=9866.73
       1 4928.11 5071.89
Encroach Node=9803.8
       1 4928.11 5091.89
Encroach Node=9740.892
       1 4948.11 5091.89
Encroach Node=9563.455
       1  4845.4 5302.33
Encroach Node=8749.762
       1 4854.63 5125.67
Encroach Node=7694.595
       1    4690    5300
Encroach Node=6926.893
       1 4742.45 5363.49
Encroach Node=6883.529
       1    4820    5345
Encroach Node=6806.5
       1    4820    5345
Encroach Node=6729.469
       1    4820    5345
Encroach Node=6546.744
       1    4500    5250
Encroach Node=5295.497
       1 4812.74  5204.5
Encroach Node=4120.306
       1 4858.43  5300.7
Encroach Node=2876.672
       1 4886.68 5401.04
Encroach Reach=B104-00-00_0029
Encroach Node=33921.09
       1 1724.93 1810.55
Encroach Node=33632.02
       1 4956.89 5047.47
Encroach Node=33611.02
       1 4956.89 5043.11
Encroach Node=33271.4
       1    4877    5123
Encroach Node=32931.84
       1    4877    5123
Encroach Node=32851.1
       1 4947.99 5052.01
Encroach Node=31595.28
       1 4908.14    5073
Encroach Node=30906.64
       1 4894.07 5055.36
Encroach Node=30886.64
       1 4894.07 5055.36
Encroach Node=30856.34
       1 4880.07 5055.36
Encroach Node=30775.48
       1 4894.07 5055.36
Encroach Node=29977.43
       1  4837.5 5167.74
Encroach Node=29937.02
       1 4877.18 5177.79
Encroach Node=29774.81
       1 4934.07  5171.1
Encroach Node=29620.56
       1 4888.28 5133.84
Encroach Node=28679.27
       1  4883.9 5118.44
Encroach Node=27313.46
       1 4819.32 5267.08
Encroach Node=25959.34
       1 4881.36 5162.94
Encroach Node=25919.28
       1 4899.63 5146.13
Encroach Node=25823.8
       1 4878.27 5146.13
Encroach Node=25728.31
       1 4878.27 5111.64
Encroach Node=25536.03
       1 4868.95  5130.5
Encroach Node=24058.15
       1 4892.12    5118
Encroach Node=24038.15
       1 4894.46 5105.25
Encroach Node=23905.5
       1 4889.93 5106.69
Encroach Node=23772.84
       1 4889.93 5106.69
Encroach Node=23692.71
       1 4869.45    5096
Encroach Node=22758.24
       1    4931 5150.56
Encroach Node=21821.68
       1 4911.22 5088.78
Encroach Node=21072.13
       1  4910.1    5126
Encroach Node=21031.83
       1  4910.1  5089.9
Encroach Node=20942.9
       1 4864.69    5141
Encroach Node=20853.92
       1 4864.69    5140
Encroach Node=20693.87
       1 4838.28 5214.05
Encroach Node=19846.57
       1  4850.5 5079.23
Encroach Node=19812.71
       1 4831.53  5138.3
Encroach Node=19737.92
       1 4831.53    5220
Encroach Node=19663.12
       1 4899.18 5148.39
Encroach Node=19580.65
       1 4760.04 5138.28
Encroach Node=19232.53
       1 4855.49 5083.37
Encroach Node=19212.44
       1  4834.9 5083.37
Encroach Node=19151.64
       1  4834.9 5103.37
Encroach Node=19090.84
       1 4900.01 5103.37
Encroach Node=19010.58
       1 4896.54    5089
Encroach Node=17730.46
       1 4932.26 5107.74
Encroach Node=16521.13
       1 4912.26 5087.74
Encroach Node=16480.97
       1 4912.26    5143
Encroach Node=16422.9
       1 4912.26    5143
Encroach Node=16364.84
       1 4912.26    5143
Encroach Node=16204.84
       1    4888    5141
Encroach Node=14932.88
       1 4902.75 5097.25
Encroach Node=13216.11
       1 4880.46 5106.61
Encroach Node=11490.4
       1 4920.32 5079.68
Encroach Node=11450.35
       1 4920.32 5079.68
Encroach Node=11295.96
       1 4920.32 5079.68
Encroach Node=11141.62
       1    4900 5089.68
Encroach Node=10978.64
       1    4911    5200
Encroach Node=9906.905
       1    4900    5200
Encroach Node=9866.73
       1 4928.11 5071.89
Encroach Node=9803.8
       1 4928.11 5091.89
Encroach Node=9740.892
       1 4948.11 5091.89
Encroach Node=9563.455
       1  4845.4 5302.33
Encroach Node=8749.762
       1 4854.63 5125.67
Encroach Node=7694.595
       1    4690    5300
Encroach Node=6926.893
       1 4742.45 5363.49
Encroach Node=6883.529
       1    4820    5345
Encroach Node=6806.5
       1    4820    5345
Encroach Node=6729.469
       1    4820    5345
Encroach Node=6546.744
       1    4500    5250
Encroach Node=5295.497
       1 4812.74  5204.5
Encroach Node=4120.306
       1 4858.43  5300.7
Encroach Node=2876.672
       1 4886.68 5401.04
Computation Interval=1HOUR
Output Interval=1HOUR
Run HTab= 0
Run UNet= 0
Run PostProcess= 0
UNET Theta= 1
UNET ZTol= 0.02
UNET ZSATol= 0.1
UNET MxIter= 20
UNET MaxInSteps= 20
UNET DtIC= 0
UNET DtMin= 0
UNET MaxCRTS= 20
UNET WFStab= 2
UNET SFStab= 1
UNET WFX= 1
UNET SFX= 1
UNET Convert EG Bridges=-1
UNET Use Existing IB Tables=-1
Instantaneous Interval=1HOUR
Write IC File= 0
IC Time=0
Write Velocity= 0
Write Detailed= 0

--- B104_00_00.f02 (steady flow) ---

Flow Title=FEMA Effective June 2007
Program Version=3.11
Number of Profiles= 4
Profile Names=10PCT_10yr, 2PCT_50yr, 1PCT_100yr, 0.2PCT_500yr
River Rch & RM=B104-00-00,B104-00-00_0029            ,33921.09
    1389    2056    2402    3321
River Rch & RM=B104-00-00,B104-00-00_0029            ,33632.02
    1389    2056    2402    3321
River Rch & RM=B104-00-00,B104-00-00_0029            ,32851.1
    1492    2202    2569    3400
River Rch & RM=B104-00-00,B104-00-00_0029            ,31595.28
    1563    2302    2684    3452
River Rch & RM=B104-00-00,B104-00-00_0029            ,30775.48
    1654    2431    2831    3517
River Rch & RM=B104-00-00,B104-00-00_0029            ,29774.81
    1728    2544    2959    3617
River Rch & RM=B104-00-00,B104-00-00_0029            ,28679.27
    1825    2693    3126    3744
River Rch & RM=B104-00-00,B104-00-00_0029            ,27313.46
    3487    5126    5639    6896
River Rch & RM=B104-00-00,B104-00-00_0029            ,25959.34
    3554    5226    5710    6916
River Rch & RM=B104-00-00,B104-00-00_0029            ,25728.31
    4183    6086    6697    8322
River Rch & RM=B104-00-00,B104-00-00_0029            ,24058.15
    4341    6191    6895    8395
River Rch & RM=B104-00-00,B104-00-00_0029            ,21072.13
    4631    6657    7457    9032
River Rch & RM=B104-00-00,B104-00-00_0029            ,21031.83
    4804    6871    7716    9243
River Rch & RM=B104-00-00,B104-00-00_0029            ,17730.46
    6520    9226   10458   12519
River Rch & RM=B104-00-00,B104-00-00_0029            ,14932.88
    6649    9396   10654   12742
River Rch & RM=B104-00-00,B104-00-00_0029            ,13216.11
    7080   10024   11330   13697
River Rch & RM=B104-00-00,B104-00-00_0029            ,11490.4
    7850   11196   12594   15558
River Rch & RM=B104-00-00,B104-00-00_0029            ,8749.762
    7937   11340   12758   15800
River Rch & RM=B104-00-00,B104-00-00_0029            ,7694.595
    8412   12119   13656   17098
Boundary for River Rch & Prof#=B104-00-00,B104-00-00_0029            , 1
Up Type= 0
Dn Type= 3
Dn Slope=0.001
Boundary for River Rch & Prof#=B104-00-00,B104-00-00_0029            , 2
Up Type= 0
Dn Type= 3
Dn Slope=0.001
Boundary for River Rch & Prof#=B104-00-00,B104-00-00_0029            , 3
Up Type= 0
Dn Type= 3
Dn Slope=0.001
Boundary for River Rch & Prof#=B104-00-00,B104-00-00_0029            , 4
Up Type= 0
Dn Type= 3
Dn Slope=0.001
Observed WS=Horsepen_Bayou  ,B104-00-00_0029            ,11450.35,0,14.35,,,
Observed WS=B104-00-00      ,B104-00-00_0029            ,11450.35,0,14.35,,,
DSS Import GetInterval= 0
DSS Import GetPeak= 0
DSS Import FillOption= 0

--- B104_00_00.f03 (steady flow) ---

Flow Title=Floodway
Version=Version 3.0.1  Mar 2001
Number of Profiles= 2
Profile Names=1PCT_100yr, 1PCTFloodway_100yrFW
River Rch & RM=B104-00-00,B104-00-00_0029            ,33921.09
    2402    2402
River Rch & RM=B104-00-00,B104-00-00_0029            ,33632.02
    2402    2402
River Rch & RM=B104-00-00,B104-00-00_0029            ,32851.1
    2569    2569
River Rch & RM=B104-00-00,B104-00-00_0029            ,31595.28
    2684    2684
River Rch & RM=B104-00-00,B104-00-00_0029            ,30775.48
    2831    2831
River Rch & RM=B104-00-00,B104-00-00_0029            ,29774.81
    2959    2959
River Rch & RM=B104-00-00,B104-00-00_0029            ,28679.27
    3126    3126
River Rch & RM=B104-00-00,B104-00-00_0029            ,27313.46
    5639    5639
River Rch & RM=B104-00-00,B104-00-00_0029            ,25959.34
    5710    5710
River Rch & RM=B104-00-00,B104-00-00_0029            ,25728.31
    6697    6697
River Rch & RM=B104-00-00,B104-00-00_0029            ,24058.15
    6895    6895
River Rch & RM=B104-00-00,B104-00-00_0029            ,21072.13
    7457    7457
River Rch & RM=B104-00-00,B104-00-00_0029            ,21031.83
    7716    7716
River Rch & RM=B104-00-00,B104-00-00_0029            ,17730.46
   10458   10458
River Rch & RM=B104-00-00,B104-00-00_0029            ,14932.88
   10654   10654
River Rch & RM=B104-00-00,B104-00-00_0029            ,13216.11
   11330   11330
River Rch & RM=B104-00-00,B104-00-00_0029            ,11490.4
   12594   12594
River Rch & RM=B104-00-00,B104-00-00_0029            ,8749.762
   12758   12758
River Rch & RM=B104-00-00,B104-00-00_0029            ,7694.595
   13656   13656
Boundary for River Rch & Prof#=B104-00-00,B104-00-00_0029            , 1
Up Type= 0
Dn Type= 3
Dn Slope=.001
Boundary for River Rch & Prof#=B104-00-00,B104-00-00_0029            , 2
Up Type= 0
Dn Type= 3
Dn Slope=.001
Observed WS=B104-00-00      ,B104-00-00_0029            ,11450.35, 0 ,14.35,
DSS Import GetInterval= 0
DSS Import GetPeak= 0
DSS Import FillOption= 0

--- B104_00_00.g01 (geometry) ---

Geom Title=B104-00-00 June 2007
Program Version=3.11

River Reach=B104-00-00      ,B104-00-00_0029
Reach XY= 30
      3182470.25       13781414.      3184623.25       13781516.
      3184865.25       13781351.        3186243.       13782527.
      3192450.25       13782896.      3194327.25       13783441.
      3194736.25       13784008.      3195319.75       13784235.
      3196587.25       13784233.      3198237.25       13783836.
        3199580.       13781775.      3200283.25       13781517.
      3200850.75       13780683.      3202487.75       13780399.
      3203586.75       13780908.      3205706.25       13780921.
        3207111.       13779934.        3207419.       13779112.
      3209033.75       13778773.       3210806.5       13779146.
      3210747.25       13779644.       3211122.5       13780225.
       3210832.5       13780663.        3210893.       13781220.
     3211349.968    13781812.263     3211741.627     13781802.71
      3211872.75       13781354.      3212113.75       13781252.
      3212656.25       13781966.      3213535.75       13782349.

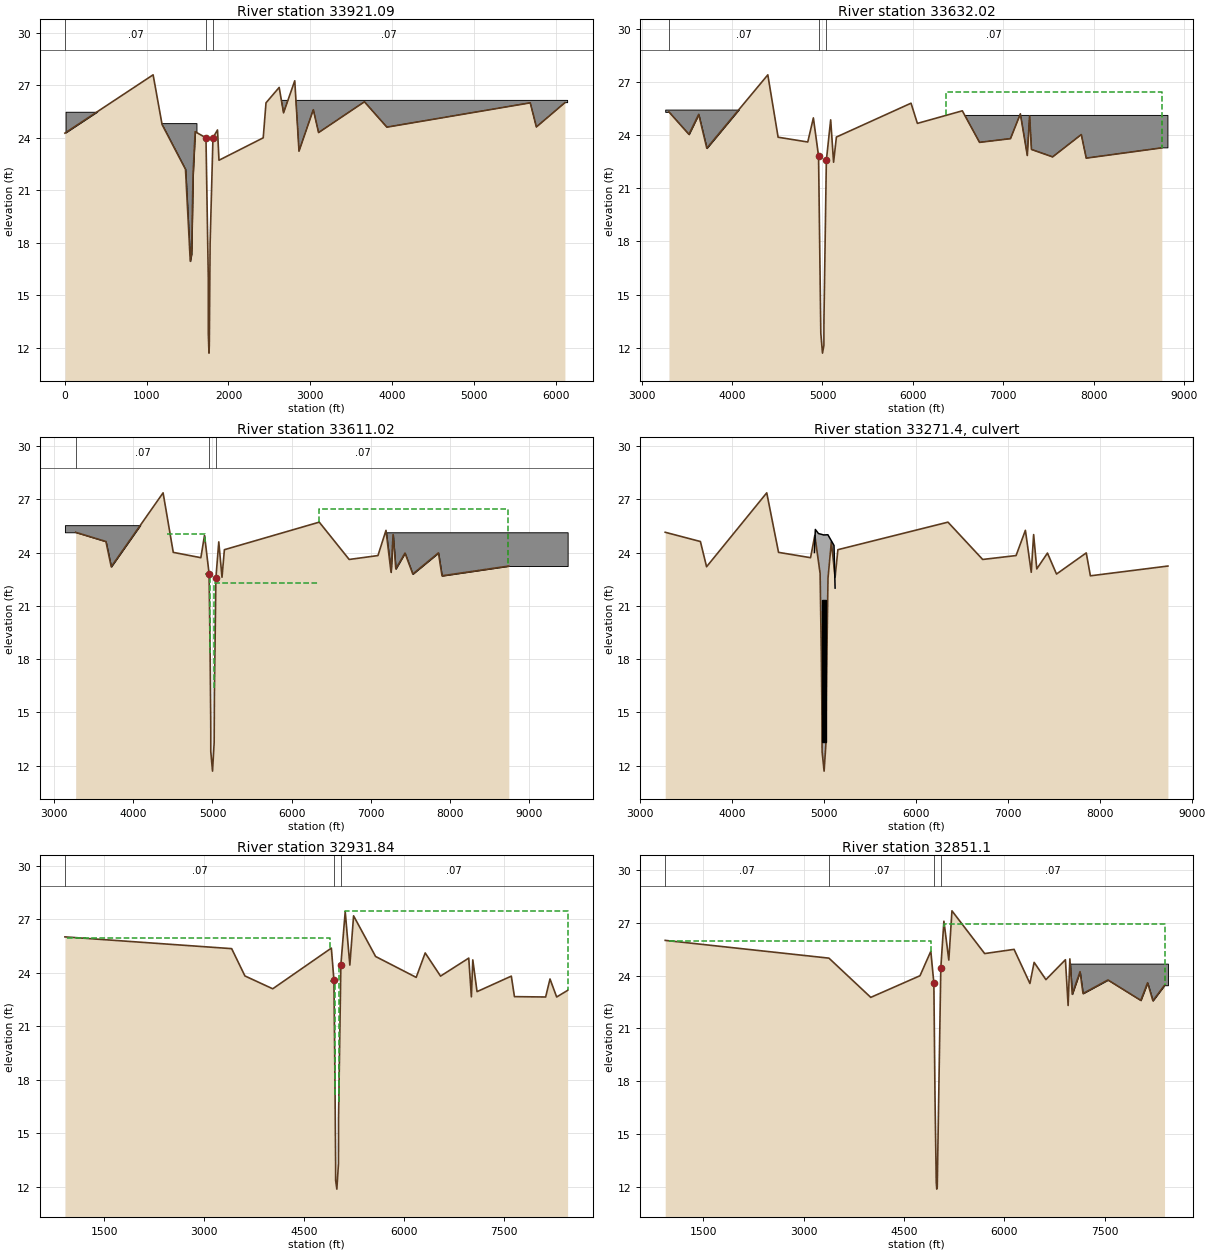
Type RM Length L Ch R = 1 ,33921.09,295.88,289.07,277.2
BEGIN DESCRIPTION:
CROSS SECTION ADDED TO EXTEND FLOODWAY TO EXISTING
END DESCRIPTION:
XS GIS Cut Line= 4
     3186738.905    13784321.496     3186793.809    13782642.596
     3186809.736    13782558.283     3187016.066    13778214.115
#Sta/Elev= 30
       0   24.27 1078.56    27.6 1188.12   24.76 1474.61    22.2 1533.03   16.95
 1548.94   17.37 1566.87    21.9 1592.57   24.35 1724.93      24 1753.37      16
 1753.53   12.82 1761.81    11.7  1765.6   12.13 1775.76      18 1810.55   24.01
 1865.98   24.45 1884.09   22.72 2425.06      24 2459.17      26 2620.12   26.88
 2673.73   25.43 2810.79   27.26 2862.77   23.24 3037.82   25.61 3102.24    24.3
 3662.71   26.06 3937.21   24.61 5691.01      26 5765.49   24.62 6114.67   26.01
#Mann= 3 , 0 , 0
       0     .07       0 1724.93    .042       0 1810.55     .07       0
#Block Obstruct= 4 ,-1
    7.96  963.59   25.49  868.03  979.52    25.3 1138.79 1608.65   24.84
 2627.99  6147.9   26.14
Bank Sta=1724.93,1810.55
XS Rating Curve= 0
Exp/Cntr=0.3,0.1

Type RM Length L Ch R = 1 ,33632.02,26.5,21,20.58
XS GIS Cut Line= 5
     3187023.753    13784330.811     3187077.938     13782673.89
     3187093.944     13782589.16     3187118.284    13781770.742
      3189024.82    13779597.291
#Sta/Elev= 30
 3301.09   25.31  3522.9   24.04 3630.54   25.17 3720.37   23.26 4395.46    27.4
 4509.33   23.88 4837.51   23.61 4899.45   24.97 4956.89   22.82 4981.87   12.82
 5000.36    11.7 5015.98   12.13 5016.53   13.57 5043.11   22.57 5091.01   24.86
 5123.15   22.47 5154.32   23.89 5980.17    25.8 6050.43   24.66  6547.6   25.37
 6738.15   23.59 7080.73    23.8 7189.92    25.2 7266.73   22.85 7291.97   25.09
 7312.78   23.19 7546.69   22.77 7864.02   24.03 7918.62    22.7 8755.06   23.28
#Mann= 3 ,-1 , 0
 3301.09     .07       0 4956.89    .042       0 5043.11     .07       0
#XS Ineff= 1 ,-1
 6372.01 8836.18   26.41
Permanent Ineff=
       F
#Block Obstruct= 2 ,-1
 3260.14 4330.44   25.44 6542.66 8822.53   25.11
Bank Sta=4956.89,5043.11
XS Rating Curve= 0
Exp/Cntr=0.5,0.3

Type RM Length L Ch R = 1 ,33611.02,681.47,679.18,657.89
XS GIS Cut Line= 5
     3187064.924    13784361.689     3187097.883     13782676.05
     3187113.888    13782591.327     3187138.062    13781778.525
     3189039.855     13779610.48
#Sta/Elev= 30
  3271.7   25.14 3654.66   24.62 3721.72    23.2 4376.33   27.36 4504.68   24.01
 4853.05   23.71 4899.45   24.97 4956.89   22.82 4970.25   18.26 4978.05   14.39
 4978.42   12.81 5000.36    11.7 5020.98    13.3 5024.01   16.07 5043.11   22.57
 5079.31    24.6 5120.09   22.61 5150.28   24.16 6347.94   25.71 6725.74   23.61
 7088.86   23.83 7190.43   25.25 7254.21   22.89 7279.86   25.01 7314.27   23.08
 7430.41   23.97  7528.9   22.79 7852.62   23.98 7897.41   22.69 8741.01   23.24
#Mann= 3 ,-1 , 0
  3271.7     .07       0 4956.89    .042       0 5043.11     .07       0
#XS Ineff= 4 ,-1
 4419.58 4909.09   25.04 4909.09    4970    22.8 5024.98  6342.8   22.28
  6342.8  8734.2   26.45
Permanent Ineff=
       F       F       F       F
#Block Obstruct= 2 ,-1
    3137 4341.64   25.54  7191.5 9483.55   25.14
Bank Sta=4956.89,5043.11
XS Rating Curve= 0
Exp/Cntr=0.5,0.3

Type RM Length L Ch R = 2 ,33271.4 ,,,
BEGIN DESCRIPTION:
Ellington Field
END DESCRIPTION:
Bridge Culvert--1,0,-1,-1, 0
Deck Dist Width WeirC Skew NumUp NumDn MinLoCord MaxHiCord MaxSubmerge Is_Ogee
56,580,2.6,0, 7, 7, , , 0.95, 0, 0,0,,
    4895    4905 4939.06 4995.92 5041.77    5108    5120
      24    25.3   25.07   24.99      25    24.4      22
               0       0       0       0       0
    4895    4905 4939.06 4995.92 5041.77    5108    5120
      24    25.3   25.07   24.99      25    24.4      22
               0       0       0       0       0
BR Coef=-1 , 0 , 0 ,, 0 ,,,0.8,0,,0,
WSPro=,,,, 1 ,,,, 0 ,,,, 0 ,,,,-1 ,-1 ,-1 , 0 , 0 , 0 , 0 , 0
Multiple Barrel Culv=2,8,9,580,0.013,0.5,1,58,1,13.33,13.33, 4,Culvert #1  , 0 ,56
4982.674 4977.67 4993.71 4988.715004.557 4999.565015.503  5010.5
Culvert Bottom n=0.013
BC Design=,, 0 ,, 0 ,,,,,,
BC HTab HWMax=27.36

Type RM Length L Ch R = 1 ,32931.84,76.52,80.74,81.36
XS GIS Cut Line= 6
 3187626.308493613786763.3443204 3187630.035738113786669.4182449
     3187786.806    13782718.828     3187772.733    13782615.774
     3187765.654    13781265.041     3189096.909     13779705.57
#Sta/Elev= 30
     906      26 3411.09   25.34 3610.51   23.81 4028.17   23.09 4908.74   25.37
 4947.99   23.57 4964.99   17.13 4973.07   13.36 4973.22   12.35 4991.53   11.86
 5015.94   13.31 5016.88   15.85 5052.01   24.44 5117.08   27.42 5186.73   24.42
 5242.89   27.18 5573.93    24.9 6183.59   23.73 6318.88    25.1 6549.26    23.8
 6973.32   24.81 7012.65   22.64 7033.92   24.71 7097.76   22.93 7612.87    23.8
 7659.68   22.65 8128.49   22.63 8193.89   23.64    8294   22.63 8458.87      23
#Mann= 3 ,-1 , 0
     906     .07       0 4947.99    .042       0 5052.01     .07       0
#XS Ineff= 5 ,-1
 5117.01 8458.87   27.46  944.06  4895.1   25.94 5020.44 5066.17   24.49
  4895.1    4965    23.5     906  944.06    23.5
Permanent Ineff=
       F       F       F       F       F
#Block Obstruct= 2 , 0
                         7034.85            24.9
Bank Sta=4947.99,5052.01
XS Rating Curve= 0
Exp/Cntr=0.5,0.3

Type RM Length L Ch R = 1 ,32851.1 ,1244.85,1255.82,1287.42
XS GIS Cut Line= 6
 3187658.682656413786735.2087943     3187785.411     13784289.64
     3187867.013    13782714.907     3187852.704    13782610.128
     3187845.808    13781294.362     3189157.754    13779757.511
#Sta/Elev= 30
     930      26 3378.85   24.99 4004.33   22.76 4740.63   23.99 4902.34   25.38
 4947.99   23.57 4964.99   17.13 4983.78   12.24 4991.53   11.86 4998.51   11.98
 5052.01   24.44 5098.08   27.09 5171.58   24.88 5218.54   27.68 5707.95   25.25
 6147.68   25.49 6384.85   23.55 6447.35   24.75 6623.94   23.77 6915.59    24.9
    6956    22.3 6981.81   24.95 7017.53   22.94 7133.82   24.22 7178.96   22.98
 7551.74   23.75    8043   22.59 8144.64   23.59 8223.72   22.57  8397.9   23.45
#Mann= 4 ,-1 , 0
     930     .07       0 3378.85     .07       0 4947.99    .042       0
 5052.01     .07       0
#XS Ineff= 2 ,-1
 5092.57  8397.9   26.94  986.01  4898.6   25.94
Permanent Ineff=
       F       F
#Block Obstruct= 1 ,-1
 6983.04 8448.57   24.68
Bank Sta=4947.99,5052.01
XS Rating Curve= 0
Exp/Cntr=0.3,0.1

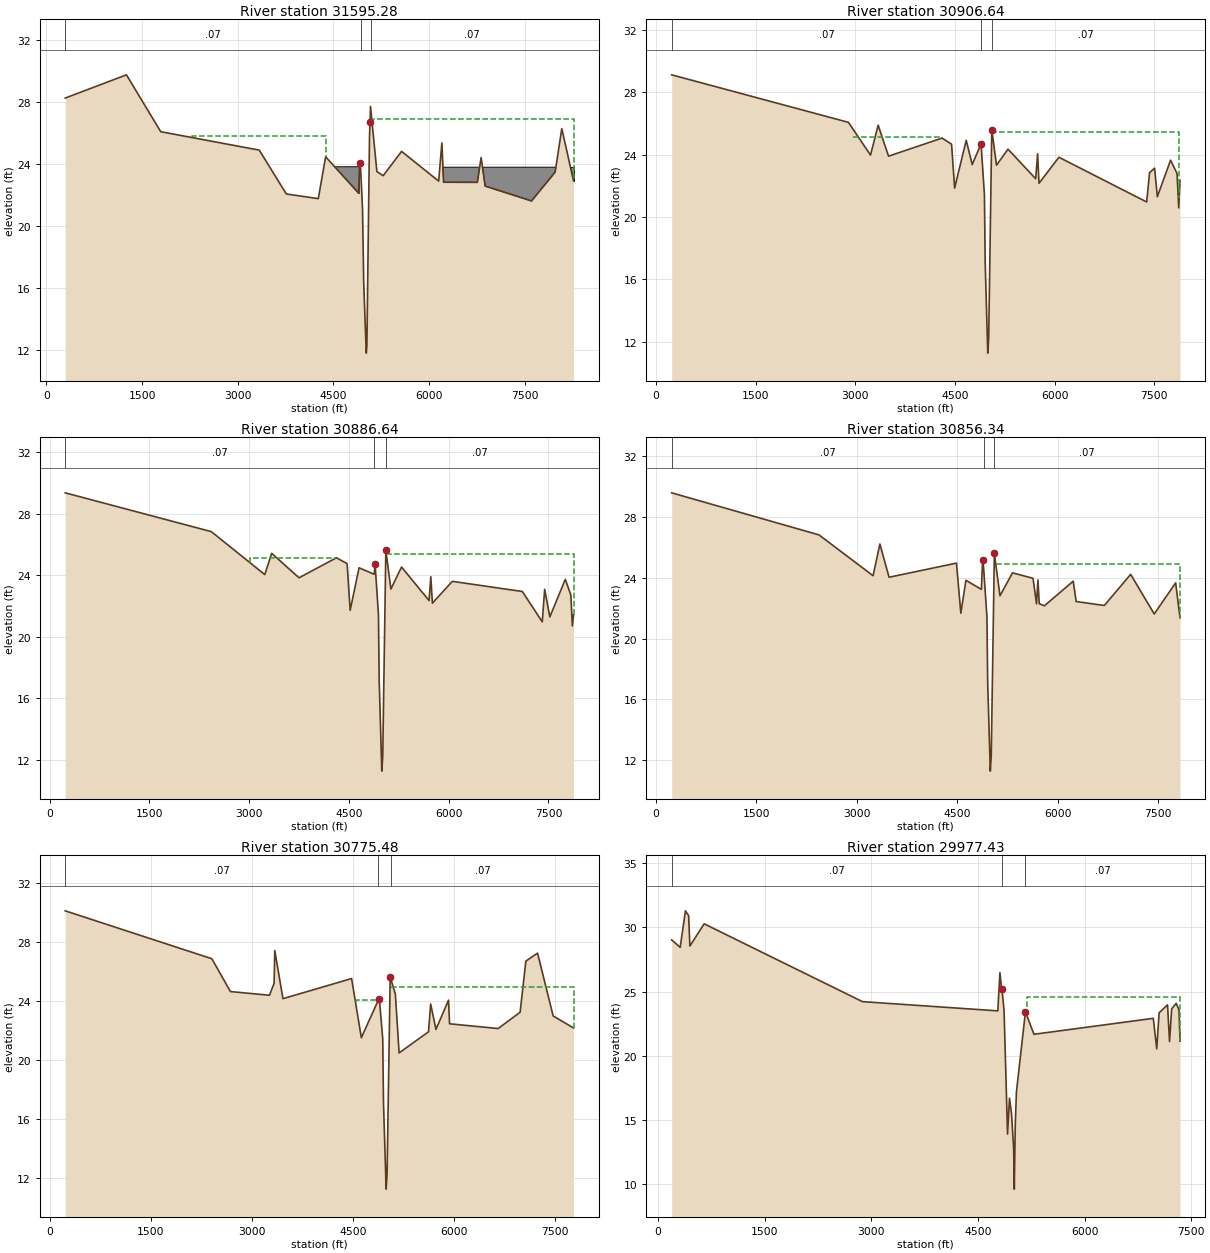
Type RM Length L Ch R = 1 ,31595.28,701.23,688.64,670.27
XS GIS Cut Line= 6
     3188860.651    13787411.948      3189020.53    13784351.396
     3189101.246    13782806.269     3189113.111     13782622.93
     3189190.093    13781085.624     3189271.818    13779453.615
#Sta/Elev= 30
  294.33   28.28 1254.49   29.78  1792.1   26.11 3336.74   24.92 3760.79   22.09
 4262.06   21.79 4377.03   24.49 4894.65   22.14 4908.14   24.06    4925   23.74
 4955.28   21.17  4974.2   16.34 5013.95   11.82 5023.92   12.27 5064.48   25.71
    5073   26.71 5080.42   27.74 5180.55   23.54 5278.51   23.27 5567.87   24.84
 6148.91   22.92 6199.43   25.39 6226.28   22.85 6755.74   22.84 6814.63   24.44
 6877.65    22.6 7604.98   21.64 7975.19    23.5 8079.18   26.31  8263.3   22.94
#Mann= 3 ,-1 , 0
  294.33     .07       0    4925    .042       0 5080.42     .07       0
#XS Ineff= 3 ,-1
 5103.89  8263.3   26.92 2276.01 4375.11   25.82  4389.2 4908.09   23.97
Permanent Ineff=
       F       F       F
#Block Obstruct= 2 ,-1
 4377.13 4911.83   23.88 6205.76  8263.3   23.82
Bank Sta=4908.14,5073
XS Rating Curve= 0
Exp/Cntr=0.3,0.1

Type RM Length L Ch R = 1 ,30906.64,20.41,20,20.03
XS GIS Cut Line= 6
     3189672.919    13787502.984     3189751.309    13784402.859
     3189791.919    13782796.863     3189799.077    13782686.661
     3189812.441    13781285.274     3189826.109    13779852.059
#Sta/Elev= 30
  236.14   29.13 2897.33   26.08 3229.54   23.98 3344.62    25.9 3501.32   23.91
 4306.67   25.07 4449.91   24.68 4496.09   21.86 4670.53   24.93  4760.6   23.37
 4894.07    24.7 4944.64   21.44 4955.66   17.14 4994.87   11.27 5008.97   12.25
 5055.36   25.61 5126.54   23.33 5299.24   24.36 5716.46   22.46 5745.22   24.06
 5766.15   22.17 6066.33   23.84 7387.29   20.97 7430.59   22.85 7506.07   23.14
 7547.93   21.31 7746.76   23.65 7844.39    22.8 7870.06   20.59 7888.93   22.36
#Mann= 3 ,-1 , 0
  236.14     .07       0 4894.07    .042       0  5057.4     .07       0
#XS Ineff= 3 ,-1
 5061.22 7877.02   25.45 2969.52 4303.72   25.17 4306.71 4889.04   24.41
Permanent Ineff=
       F       F       F
#Block Obstruct= 2 , 0
                         5634.09           23.21
Bank Sta=4894.07,5055.36
XS Rating Curve= 0
Exp/Cntr=0.3,0.1

Type RM Length L Ch R = 1 ,30886.64,32.13,30.31,35.2
XS GIS Cut Line= 6
     3189697.132    13787505.698     3189773.113    13784388.784
     3189811.894    13782797.894     3189819.071    13782687.405
      3189832.44    13781285.465     3189845.974    13779866.339
#Sta/Elev= 30
  235.76   29.35 2431.59   26.83 3235.64   24.04  3339.8   25.42 3750.32   23.83
  4312.8   25.13 4473.12   24.75 4519.26   21.72    4653   24.48 4880.07   24.06
 4894.07    24.7 4944.64   21.44 4955.66   17.14 4994.87   11.27 5008.97   12.25
 5055.36   25.61 5131.64    23.1 5291.38   24.53 5705.45   22.35 5731.62    23.9
 5755.14   22.18 6054.55    23.6 7107.51   22.94  7406.7   20.97 7442.88   23.08
  7520.6   21.29 7753.45   23.73 7836.68   22.71 7859.07    20.7 7876.89   21.43
#Mann= 3 ,-1 , 0
  235.76     .07       0 4880.07    .042       0 5055.36     .07       0
#XS Ineff= 4 ,-1
 5063.22 7876.89   25.38 3017.39  4310.2   25.11  4310.2 4891.93   24.51
  235.76 3017.39   24.51
Permanent Ineff=
       F       F       F       F
#Block Obstruct= 2 , 0
                         5081.58           23.34
Bank Sta=4894.07,5055.36
XS Rating Curve= 0
Exp/Cntr=0.3,0.1

Type RM Length L Ch R = 1 ,30856.34,81.14,80.86,80.57
XS GIS Cut Line= 4
     3189725.227    13787508.846     3189802.773     13784444.03
     3189880.935    13781354.851     3189917.299     13779917.61
#Sta/Elev= 30
  234.98    29.6 2435.12   26.83 3243.55   24.14 3345.52   26.23 3482.43   24.04
 4489.62   24.97  4554.7   21.67 4630.78   23.84 4861.49   23.24 4880.07   25.15
 4894.07    24.7 4944.64   21.44 4955.66   17.14 4994.87   11.27 5008.97   12.25
 5055.36   25.61 5139.68   22.82 5326.56   24.33 5633.11   23.97 5685.28   22.29
 5706.94   23.86 5725.63    22.3 5803.47   22.16 6233.52   23.78 6277.97   22.44
 6698.42   22.18 7091.47   24.23 7443.65   21.62 7763.74   23.67 7828.65   21.37
#Mann= 3 ,-1 , 0
  234.98     .07       0 4894.07    .042       0 5055.36     .07       0
#XS Ineff= 2 , 0
         4878.85   24.94  5074.8           24.94
Permanent Ineff=
       F       F
#Block Obstruct= 2 , 0
                         5112.56            23.2
Bank Sta=4880.07,5055.36
XS Rating Curve= 0
Exp/Cntr=0.3,0.1

Type RM Length L Ch R = 1 ,30775.48,846.33,798.05,752.75
XS GIS Cut Line= 4
     3189808.622    13787518.193     3189885.114    13784423.445
      3189960.91    13781356.837       3189995.1    13779973.536
#Sta/Elev= 30
  230.32   30.09 2407.63   26.85  2683.3   24.63 3262.71   24.38 3331.41   25.18
 3341.96    27.4 3463.04   24.15 4482.31   25.51 4627.12   21.51 4880.07   24.06
 4894.07   24.16 4944.64   21.44 4955.66   17.14 4994.87   11.27 5008.97   12.25
 5055.36   25.61 5074.28   25.34 5132.34   24.44 5187.53   20.48 5624.43   21.91
 5655.94   23.79 5734.83   22.07 5921.12   24.05  5936.8   22.45 6658.01   22.13
 6984.08   23.23 7069.73   26.69 7243.27   27.23 7474.94   22.98 7777.28   22.17
#Mann= 3 ,-1 , 0
  230.32     .07       0 4880.07    .042       0 5074.28     .07       0
#XS Ineff= 3 ,-1
  230.32  4466.2   25.32 5072.26 7777.28   24.96 4540.79 4885.78   24.08
Permanent Ineff=
       F       F       F
#Block Obstruct= 2 , 0
                         5100.23           23.12
Bank Sta=4894.07,5055.36
XS Rating Curve= 0
Exp/Cntr=0.3,0.1

Type RM Length L Ch R = 1 ,29977.43,43.22,40.41,41.18
XS GIS Cut Line= 6
     3190730.291    13787615.977     3190749.698     13784444.03
     3190758.991     13782925.05     3190690.086     13782720.63
     3190691.727     13781470.98     3190693.034    13780475.235
#Sta/Elev= 30
   190.2   29.02  310.16   28.44  383.68   31.28  429.06    30.9  446.25   28.54
  647.03   30.27 2873.73   24.22 4778.76    23.5 4808.76   26.47 4834.97   25.03
  4837.5    25.2 4866.97   23.52 4915.97   13.92 4943.14   16.71 4971.61   15.51
 5002.36   12.76 5010.53    9.64    5025   14.72    5041    17.2 5167.74   23.43
 5287.42   21.68 6966.39   22.92 7015.17   20.55  7048.5   23.35 7166.84   23.97
 7195.15   21.12 7225.16   23.66  7289.6   24.09 7327.82   23.58 7342.33   21.14
#Mann= 3 ,-1 , 0
   190.2     .07       0 4834.97    .042       0 5167.74     .07       0
#XS Ineff= 2 ,-1
 1583.62 4814.56    25.7 5186.17 7342.33   24.61
Permanent Ineff=
       F       F
#Block Obstruct= 2 , 0
                         5174.83            22.6
Bank Sta=4837.5,5167.74
XS Rating Curve= 0
Exp/Cntr=0.3,0.1

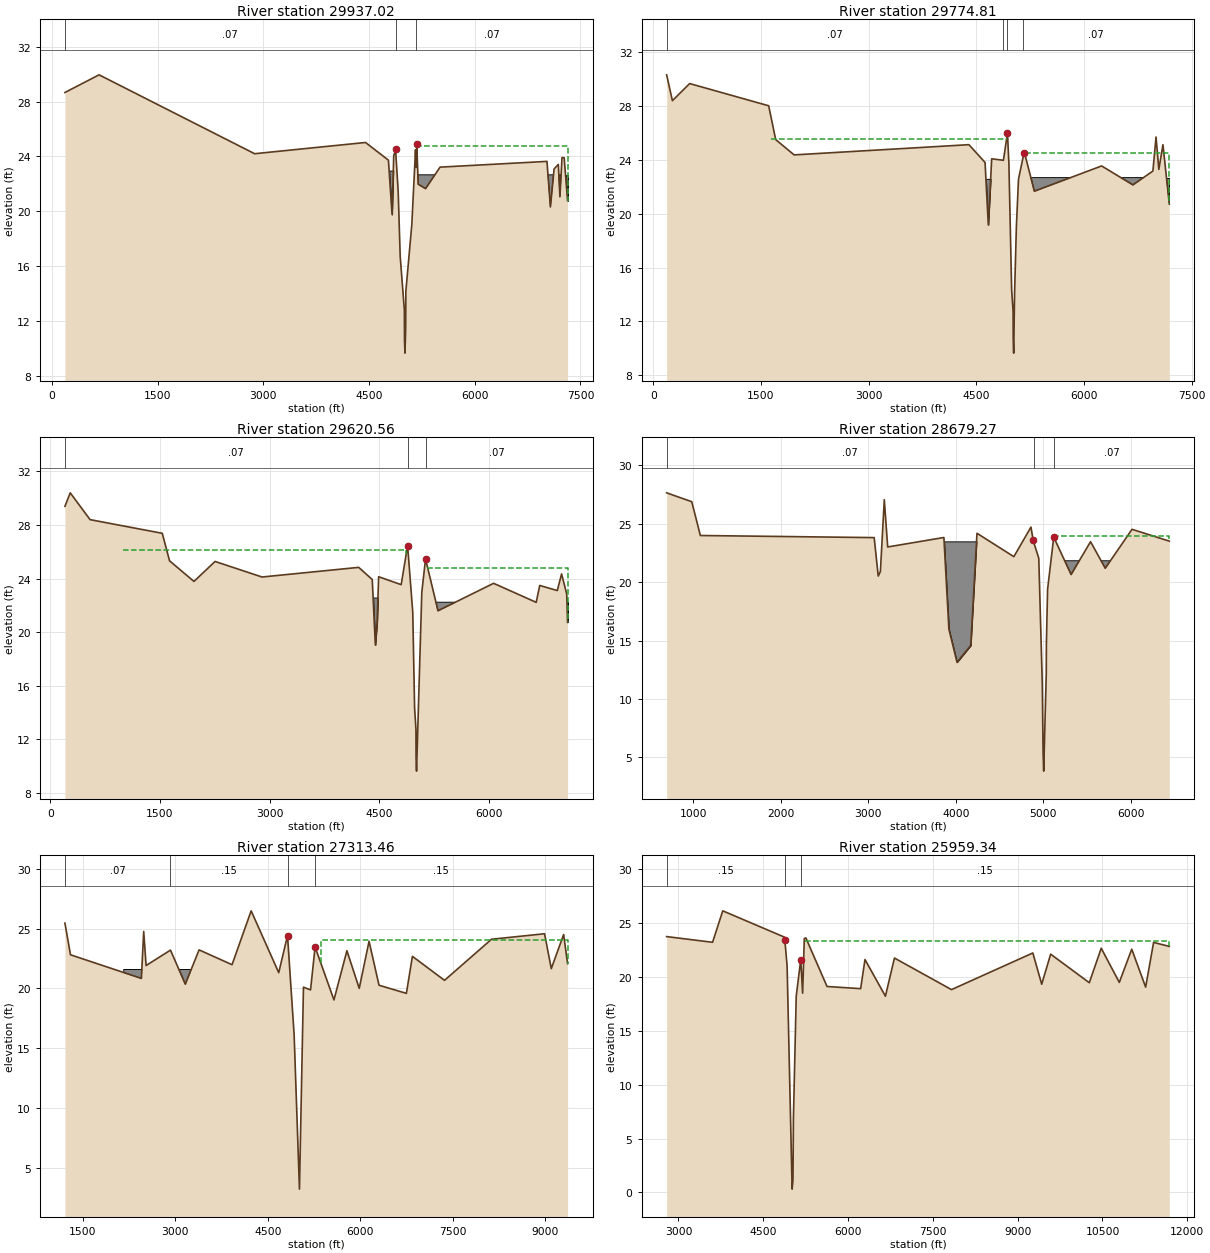
Type RM Length L Ch R = 1 ,29937.02,122.02,162.21,188.75
XS GIS Cut Line= 6
     3190805.608    13787623.956     3190801.161    13784454.323
     3190799.006    13782918.534     3190730.095    13782714.095
     3190731.727    13781471.032     3190732.996    13780503.961
#Sta/Elev= 30
  186.37   28.67  670.76   29.96 2877.83    24.2 4451.01   25.02 4776.16   23.73
 4827.83   19.76 4851.27   24.03 4877.18   24.51 4914.32   21.49 4943.14   16.71
 5002.36   12.76 5004.07   10.63 5010.53    9.64 5021.18   11.45  5023.5   14.17
 5107.87   19.02 5160.47   24.49 5169.13    23.2 5177.79   24.91 5199.13   21.97
 5303.49   21.65 5508.51   23.22 7025.47   23.64  7074.4   20.32  7126.7   23.09
  7186.8   23.42 7209.14   21.06 7238.94   23.92 7269.35   23.91 7317.67   20.77
#Mann= 3 ,-1 , 0
  186.37     .07       0 4877.18    .042       0 5160.47     .07       0
#XS Ineff= 2 ,-1
 2454.49 4434.44   24.86 5179.22 7317.67   24.74
Permanent Ineff=
       F       F
#Block Obstruct= 2 ,-1
 4696.25 4869.17   22.97 5185.93 7317.67   22.66
Bank Sta=4877.18,5177.79
XS Rating Curve= 0
Exp/Cntr=0.3,0.1

Type RM Length L Ch R = 1 ,29774.81,151.68,154.25,156.81
XS GIS Cut Line= 4
     3190932.186    13787637.365     3190924.673     13784598.42
     3190917.294    13781613.776     3190914.873      13780634.7
#Sta/Elev= 30
  185.66   30.32  265.83    28.4   506.5   29.67 1607.15   28.02  1704.6   25.51
 1961.54   24.37 4396.61   25.13 4621.82   23.81 4666.93   19.17 4714.22   24.08
 4877.46   23.97 4934.07      26    4954   23.71    4992   14.36 5012.36   12.76
 5014.07   10.63 5020.53    9.64  5033.5   14.17    5058   19.02 5087.54   22.56
 5150.66   24.17  5171.1   24.53 5308.66   21.67 6245.84   23.55 6681.92   22.14
 6960.03   23.17 7003.59    25.7 7042.81   23.29 7100.06   25.13 7188.34   20.73
#Mann= 4 ,-1 , 0
  185.66     .07       0 4877.46    .042       0 4934.07    .032       0
 5150.66     .07       0
#XS Ineff= 2 ,-1
 1645.51 4921.93   25.57 5172.68 7188.34   24.52
Permanent Ineff=
       F       F
#Block Obstruct= 2 ,-1
 4477.82 4796.36   22.59 5230.77 7188.34   22.68
Bank Sta=4934.07,5171.1
XS Rating Curve= 0
Exp/Cntr=0.3,0.1

Type RM Length L Ch R = 1 ,29620.56,936.04,941.29,944.92
XS GIS Cut Line= 4
     3191060.908    13787628.845      3191068.77    13784742.517
     3191077.293     13781613.62     3191079.637    13780753.138
#Sta/Elev= 30
  200.74   29.39  273.48    30.4  545.09    28.4 1532.63   27.38 1631.86   25.33
 1966.14   23.79 2254.38   25.28 2897.09   24.12 4219.52   24.84 4404.81   23.93
 4447.13   19.05  4472.1   20.79    4492   24.14 4800.73   23.55 4888.28   26.47
    4959   21.49    4984   14.36 5002.36   12.76 5004.07   10.63 5010.53    9.64
 5082.51   22.98 5133.84   25.47 5304.14    21.6 6064.48   23.65 6647.59   22.23
 6695.83   23.49 6935.93   23.11 6994.73   24.35    7065   22.85 7076.47   20.74
#Mann= 3 , 0 , 0
  200.74     .07       0 4888.28    .032       0 5133.84     .07       0
#XS Ineff= 3 ,-1
  200.74  992.04   25.41  992.04 4869.17   26.14 5156.18 7076.47   24.79
Permanent Ineff=
       F       F       F
#Block Obstruct= 2 ,-1
 4232.08 4805.46   22.59 5240.09 7076.47   22.24
Bank Sta=4888.28,5133.84
XS Rating Curve= 0
Exp/Cntr=0.3,0.1

Type RM Length L Ch R = 1 ,28679.27,1239.59,1365.81,1415.65
XS GIS Cut Line= 4
     3191961.233    13787175.139     3191984.817    13784999.834
     3192016.421    13782084.831     3192023.503    13781431.621
#Sta/Elev= 30
  694.98   27.63  982.02   26.87 1080.31   23.98 3066.65    23.8 3112.87   20.51
 3137.55    20.9 3182.07   27.04 3221.09      23 3863.18   23.81 3920.41   15.97
 4013.11   13.14 4170.01   14.58 4241.51   24.17 4662.75   22.17 4858.24    24.7
  4883.9   23.57    4888   23.44  4947.5   22.04 4987.76   11.25 4996.86    5.42
 5003.65    3.83    5033    12.1 5034.51   14.75 5048.17   19.38 5118.44   23.84
 5317.13   20.64 5538.98   23.45  5707.4   21.18 6012.93   24.51 6438.84    23.5
#Mann= 3 ,-1 , 0
  694.98     .07       0    4888    .032       0 5118.44     .07       0
#XS Ineff= 2 , 0
         4859.92   24.16 5119.78           23.96
Permanent Ineff=
       F       F
#Block Obstruct= 2 ,-1
 3849.64 4252.86   23.48 5221.45 5890.44   21.82
Bank Sta=4883.9,5118.44
XS Rating Curve= 0
Exp/Cntr=0.3,0.1

Type RM Length L Ch R = 1 ,27313.46,925.62,1354.12,1832.65
XS GIS Cut Line= 6
     3192333.995    13786927.854     3192736.182    13785390.955
     3193268.173    13783358.023     3193302.494    13783153.008
     3193528.089    13780865.664     3193720.583    13778913.931
#Sta/Elev= 30
 1206.74   25.46 1297.16   22.81 2447.62   20.83 2485.42   24.76  2524.1   21.91
 2919.83    23.2 3160.75   20.35 3383.88   23.22 3919.02   21.98 4229.29   26.49
  4676.8   21.31 4819.32   24.42  4926.8    16.1 5013.08    3.19 5078.16    20.1
 5192.85   19.87 5267.08   23.46 5572.89   19.03  5783.4   23.15 5983.17      20
 6142.66   23.94  6304.5   20.26 6748.54   19.58 6846.23   22.68 7367.48   20.67
 8129.99   24.11 8990.95   24.57 9100.19   21.65  9300.9   24.51 9364.29   22.07
#Mann= 4 ,-1 , 0
 1206.74     .07       0 2919.83     .15       0 4819.32    .032       0
 5267.08     .15       0
#XS Ineff= 2 , 0
         4790.21   23.67 5361.31           24.02
Permanent Ineff=
       F       F
#Block Obstruct= 1 ,-1
 2161.55 3367.46   21.58
Bank Sta=4819.32,5267.08
XS Rating Curve= 0
Exp/Cntr=0.3,0.1

Type RM Length L Ch R = 1 ,25959.34,42.69,40.06,40.2
XS GIS Cut Line= 6
     3193003.303    13785142.907     3193452.909     13784295.29
     3194141.842    13783854.427     3195196.729     13783267.53
     3196443.827    13782077.117     3197956.911    13778178.783
#Sta/Elev= 30
  2790.6   23.74 3603.05   23.21 3783.12   26.13 4878.49   23.68 4881.36    23.4
  4921.7      21  5010.2     .31 5025.06    1.15 5033.22     6.9 5082.54    18.2
 5162.94   21.61    5196   18.49  5225.7   23.56 5253.14   23.62 5627.76   19.11
 6222.27   18.91 6299.03   21.61 6660.54   18.21 6820.15   21.75 7829.21   18.82
  9268.1   22.22 9425.08   19.32 9583.37   22.1110266.97   19.4610477.84   22.66
10797.46   19.4911017.55   22.5711263.63   19.0511404.06    23.211681.58   22.83
#Mann= 3 ,-1 , 0
  2790.6     .15       0 4878.49    .032       0 5162.94     .15       0
#XS Ineff= 2 , 0
         4773.89   23.67 5240.09           23.31
Permanent Ineff=
       F       F
Bank Sta=4881.36,5162.94
XS Rating Curve= 0
Exp/Cntr=0.5,0.3