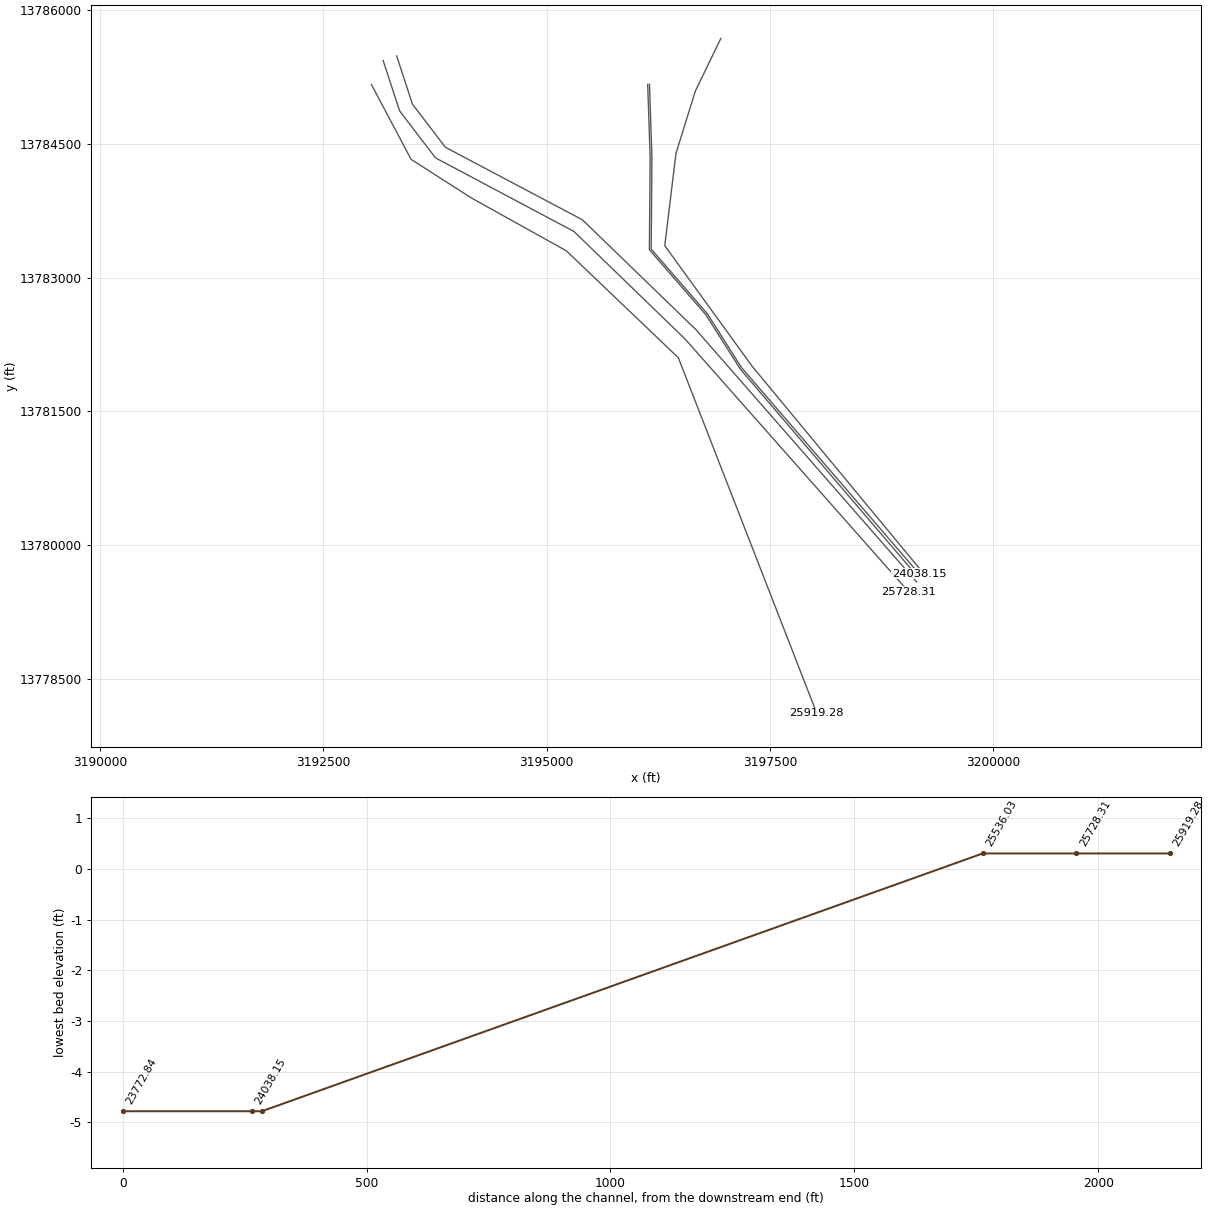
HEC-RAS study B104_00_00.prj: B104-00-00

--- B104_00_00.g01 (geometry) --- (continued)

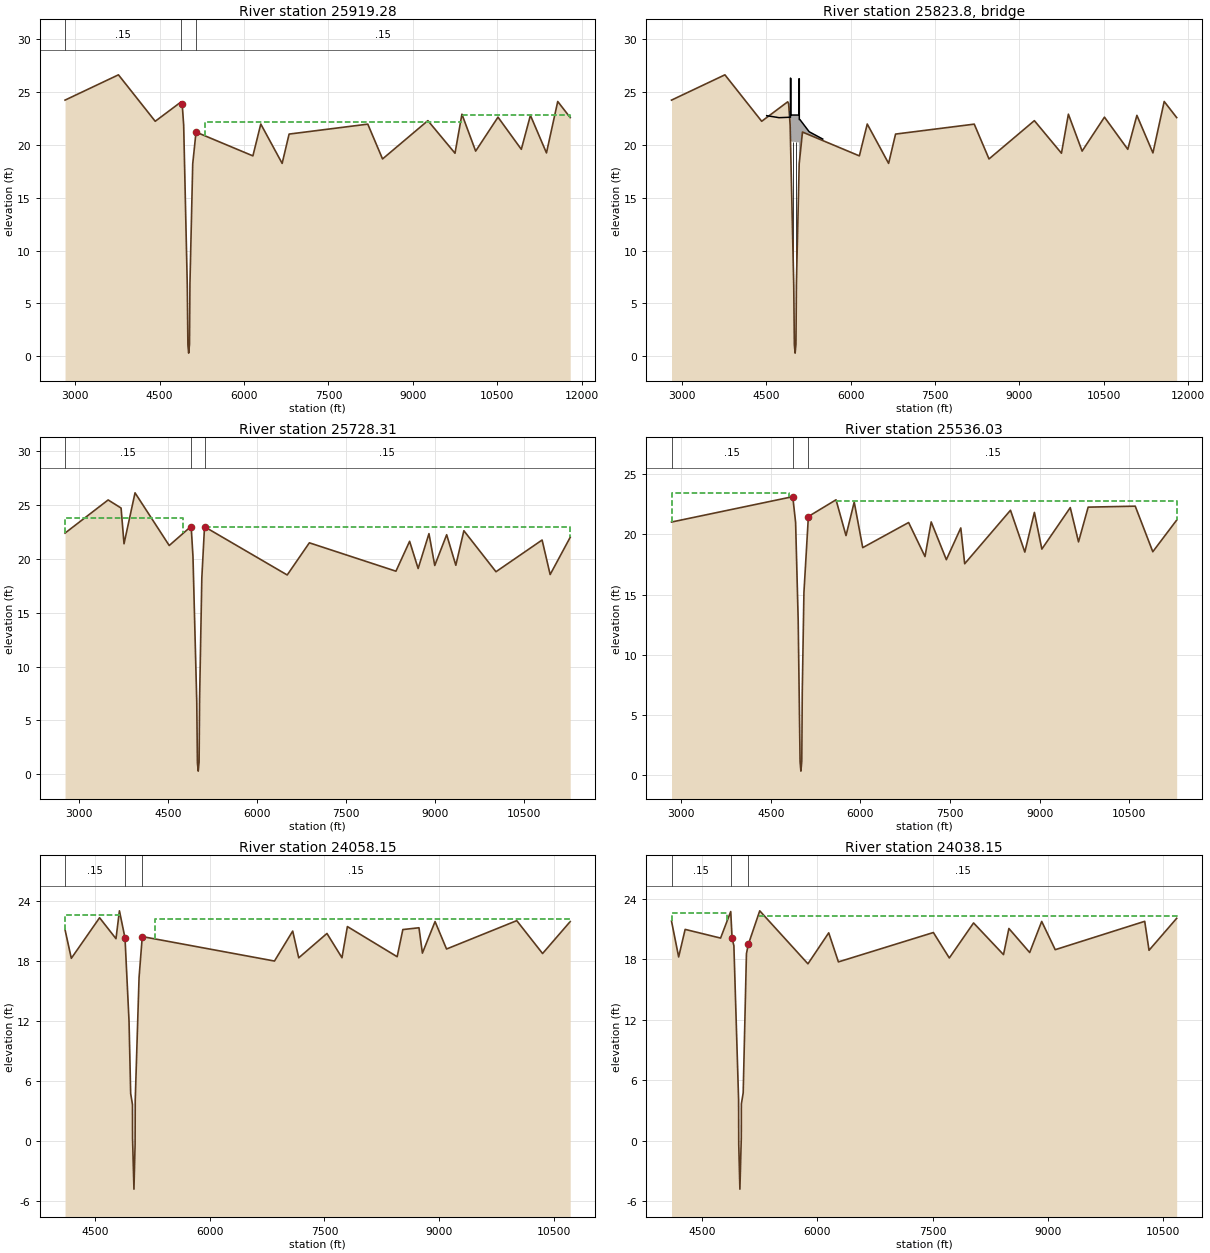
Type RM Length L Ch R = 1 ,25919.28,160.83,190.97,235.12
XS GIS Cut Line= 6
      3193038.64    13785161.651     3193483.419    13784323.133
     3194161.525    13783889.291     3195220.685     13783299.96
     3196475.869     13782101.83     3198026.625    13778119.029
#Sta/Elev= 30
 2818.77   24.22 3767.74   26.61 4421.07   22.22 4883.31   24.06 4899.63    23.9
  4926.7   21.85 4990.72    6.71 5001.65    1.09  5015.2     .31 5030.06    1.15
 5038.22     6.9 5087.54    18.2 5145.96    21.2 5146.13    21.2 6156.68   18.95
 6296.91   21.96 6676.42   18.24 6799.92   21.01 8198.18   21.95 8460.49   18.66
 9266.26   22.28 9747.95    19.2 9870.92   22.8910114.86    19.410511.84   22.61
10926.26   19.5711088.11   22.7811373.15   19.2311573.24   24.0911795.02   22.57
#Mann= 3 ,-1 , 0
 2818.77     .15       0 4883.31    .032       0 5145.96     .15       0
#XS Ineff= 3 ,-1
 4138.79 4866.89   23.67 9883.0611795.02   22.81 5308.73  9877.5   22.11
Permanent Ineff=
       F       F       F
#Block Obstruct= 1 ,-1
 4787.26 4798.63   21.71
Bank Sta=4899.63,5146.13
XS Rating Curve= 0
Exp/Cntr=0.5,0.3

Type RM Length L Ch R = 3 ,25823.8 ,,,
BEGIN DESCRIPTION:
Space Center Blvd.
END DESCRIPTION:
Bridge Culvert--1,0,-1,-1, 0
Deck Dist Width WeirC Skew NumUp NumDn MinLoCord MaxHiCord MaxSubmerge Is_Ogee
54,100,2.6,0, 14, 14, , , 0.95, 0, 0,0,,
    4510    4730 4912.76 4932.43 4932.43 4938.56 4938.58 5082.86 5082.87  5089.4
  5089.4 5099.03    5265    5506
   22.75   22.56    22.6    22.6    26.3   26.25   22.81   22.81   26.24   26.24
   22.39   22.39   21.23   20.54
                                               0   20.31   20.22       0
                                
    4490    4710 4892.76 4912.43 4912.43 4918.56 4918.58 5062.86 5062.87  5069.4
  5069.4 5079.03    5245    5486
   22.75   22.56    22.6    22.6    26.3   26.25   22.81   22.81   26.24   26.24
   22.39   22.39   21.23   20.54
                                               0   20.31   20.22       0
                                
Pier Skew, UpSta & Num, DnSta & Num=  ,4985, 4 ,4965, 4 , 3 , 3 , 0 ,,
     1.4     1.4     2.5     2.5
       0   17.81   17.81   20.31
     1.4     1.4     2.5     2.5
       0   17.81   17.81   20.31
Pier Skew, UpSta & Num, DnSta & Num=  ,5037, 4 ,5017, 4 , 3 , 3 , 0 ,,
     1.4     1.4     2.5     2.5
       0   17.81   17.81   20.31
     1.4     1.4     2.5     2.5
       0   17.81   17.81   20.31
BR Coef=-1 , 1 , 0 ,, 0 ,,,0.8,0,2,0,
WSPro=,,,, 1 ,,,, 0 ,,,, 0 ,,,,-1 ,-1 ,-1 , 0 , 0 , 0 , 0 , 0
BC Design=,, 0 ,, 0 ,,,,,,
BC HTab HWMax=26.61

Type RM Length L Ch R = 1 ,25728.31,240.1,192.28,203.91
XS GIS Cut Line= 6
     3193169.586    13785431.623     3193354.954    13784865.219
     3193756.586    13784340.008     3195306.473    13783516.148
     3196551.941    13782311.027     3199052.405    13779483.416
#Sta/Elev= 30
 2757.73   22.36 3484.94   25.43 3703.48   24.68 3752.98   21.37 3938.84   26.09
 4515.88   21.21 4878.27   22.95 4889.16    22.7  4916.7    20.2 4980.72    6.71
 4991.65    1.09  5005.2     .31 5020.06    1.15 5028.22     6.9    5066    18.2
 5111.64   22.95 6507.21   18.48 6880.96   21.46 8342.45   18.83 8573.09    21.6
 8716.96   19.08 8899.66   22.31 8997.47   19.36 9198.36   22.21 9352.98   19.38
 9488.85   22.5810030.54   18.7810809.21   21.7210944.96   18.5211283.46   21.97
#Mann= 3 ,-1 , 0
 2757.73     .15       0 4889.16    .032       0 5111.64     .15       0
#XS Ineff= 2 , 0
         4750.58   23.75 5113.82           22.91
Permanent Ineff=
       F       F
Bank Sta=4878.27,5111.64
XS Rating Curve= 0
Exp/Cntr=0.5,0.3

Type RM Length L Ch R = 1 ,25536.03,1979.82,1477.88,874.13
XS GIS Cut Line= 6
     3193321.649    13785481.389     3193498.563    13784940.819
     3193867.263    13784458.672     3195400.715    13783647.294
      3196671.45    13782417.981     3199142.036    13779592.965
#Sta/Elev= 30
 2839.66   21.03 4868.95   23.14  4916.7      21    4960   12.85 4991.65    1.09
  5005.2     .31 5020.06    1.15 5028.22     6.9    5056   15.16  5130.5   21.49
 5593.29   22.88 5760.28    19.9 5897.83   22.69 6040.24    18.9 6808.47   20.99
 7082.44   18.16  7186.2   21.04 7440.08    17.9 7681.57   20.54 7746.88   17.56
 8513.39   22.01 8753.52   18.53 8913.66   21.83 9038.42   18.78 9513.91   22.23
 9652.06   19.38 9813.67   22.2710601.43   22.3510895.37   18.5611295.02   21.19
#Mann= 3 ,-1 , 0
 2839.66     .15       0 4868.95    .032       0  5130.5     .15       0
#XS Ineff= 2 , 0
         4808.86   23.46 5589.74            22.8
Permanent Ineff=
       F       F
Bank Sta=4868.95,5130.5
XS Rating Curve= 0
Exp/Cntr=0.3,0.1

Type RM Length L Ch R = 1 ,24058.15,20.02,20,20
XS GIS Cut Line= 6
     3196132.575    13785163.045     3196160.029    13784347.246
     3196151.521    13783311.577     3196783.093    13782584.311
     3197171.754    13781972.386     3199161.954     13779642.76
#Sta/Elev= 30
 4108.45    21.1 4190.46   18.25 4559.85    22.3 4774.37   20.21  4819.4   22.99
 4892.12   20.29  4944.9   11.99 4966.32    4.76 4989.97    3.66 4991.06      .3
 5009.17   -4.78 5024.07    -.34 5026.01    4.07 5075.95   16.32    5118   20.42
 6846.48   17.98 7084.71   20.97 7163.49    18.3 7532.38   20.73 7728.89   18.31
 7799.66   21.42 8450.27   18.41 8524.54   21.12 8735.45    21.3 8780.32   18.77
 8945.71   21.92 9095.78   19.1810013.63   22.0110351.32   18.7310712.55   21.92
#Mann= 3 , 0 , 0
 4108.45     .15       0 4892.12    .032       0    5118     .15       0
#XS Ineff= 2 , 0
         4824.01   22.54 5285.91           22.18
Permanent Ineff=
       F       F
Bank Sta=4892.12,5118
XS Rating Curve= 0
Exp/Cntr=0.5,0.3

Type RM Length L Ch R = 1 ,24038.15,388.38,265.31,208.62
XS GIS Cut Line= 6
     3196152.564    13785163.718     3196180.032      13784347.5
     3196171.582    13783318.978     3196799.174    13782596.296
     3197181.667    13781994.082     3199171.913    13779682.596
#Sta/Elev= 30
 4107.02   21.77 4199.88   18.22 4284.18   20.95 4744.81   20.09 4876.77   22.72
 4894.46   20.06 4917.75   19.33 4978.99    4.07 4980.93    -.34 4995.83   -4.78
 5013.94      .3 5015.03    3.66 5038.68    4.76 5080.95   18.55 5105.25   19.46
 5253.71   22.79 5880.37   17.54 6150.51   20.61 6276.49   17.73 7510.79   20.64
 7717.82   18.12 8033.13   21.59 8422.25   18.45  8492.3   21.04  8762.6   18.66
 8918.77   21.74 9094.41   18.9410257.53   21.7510313.82   18.8810673.08   22.05
#Mann= 3 ,-1 , 0
 4107.02     .15       0 4876.77    .032       0 5105.25     .15       0
#XS Ineff= 2 , 0
         4832.17   22.62 5248.25           22.27
Permanent Ineff=
       F       F
Bank Sta=4894.46,5105.25
XS Rating Curve= 0
Exp/Cntr=0.5,0.3

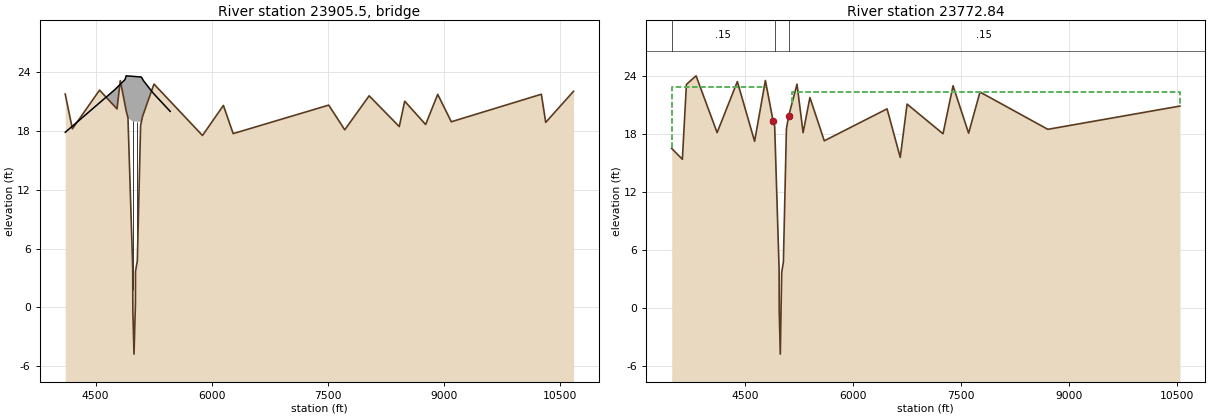
Type RM Length L Ch R = 3 ,23905.5 ,,,
BEGIN DESCRIPTION:
Clear Lake Blvd.
END DESCRIPTION:
Bridge Culvert--1,0,-1,-1, 0
Deck Dist Width WeirC Skew NumUp NumDn MinLoCord MaxHiCord MaxSubmerge Is_Ogee
81,115,2.6,0, 10, 10, , , 0.95, 0, 0,0,,
    4108    4744 4879.72 4894.44 4894.45 5090.81 5090.82 5117.29    5245    5463
   17.87   22.19   23.25   23.63   23.63   23.51   23.51   23.14   21.85      20
                               0   19.01   18.93       0
    4108    4744 4879.72 4894.44 4894.45 5090.81 5090.82 5117.29    5245    5463
   17.87   22.19   23.25   23.63   23.63   23.51   23.51   23.14   21.85      20
                               0   19.01   18.93       0
Pier Skew, UpSta & Num, DnSta & Num=  ,4980, 4 ,4980, 4 , 3 , 3 , 0 ,,
     1.4     1.4       3       3
       0   16.19   16.19   19.19
     1.4     1.4       3       3
       0   16.19   16.19   19.19
Pier Skew, UpSta & Num, DnSta & Num=  ,5038, 4 ,5038, 4 , 3 , 3 , 0 ,,
     1.4     1.4       3       3
       0   16.19   16.19   19.19
     1.4     1.4       3       3
       0   16.19   16.19   19.19
BR Coef=-1 , 1 , 0 ,, 0 ,,,0.8,0,2,0,
WSPro=,,,, 1 ,,,, 0 ,,,, 0 ,,,,-1 ,-1 ,-1 , 0 , 0 , 0 , 0 , 0
BR U #Sta/Elev= 30
 4107.02   21.77 4199.88   18.22 4550.64   22.17 4776.13   20.25 4818.64   23.14
 4894.46   20.06 4917.75   19.33 4978.99    4.07 4980.93    -.34 4995.83   -4.78
 5013.94      .3 5015.03    3.66 5038.68    4.76 5080.95   18.55 5105.25   19.46
 5253.71   22.79 5880.37   17.54 6150.51   20.61 6276.49   17.73 7510.79   20.64
 7717.82   18.12 8033.13   21.59 8422.25   18.45  8492.3   21.04  8762.6   18.66
 8918.77   21.74 9094.41   18.9410257.53   21.7510313.82   18.8810673.08   22.05
BR U #Mann= 3
 4107.02     .15 4894.46    .015 5105.25     .15
BR D #Sta/Elev= 30
 3481.57   16.52 3630.19    15.4 3686.34   23.15 3820.41   24.04 4113.08   18.16
 4394.02   23.44 4633.96   17.26 4783.64   23.56 4889.93    19.4 4924.05   16.32
 4973.99    4.07 4975.93    -.34 4990.83   -4.78 5010.03    3.66 5033.68    4.76
 5075.95   18.55 5106.69   19.87 5222.97   23.18 5307.57   18.15 5402.07   21.79
 5601.99   17.31 6474.24   20.62 6657.32   15.59 6752.27   21.11 7251.48   18.04
  7390.8   23.01 7607.34    18.1 7765.23   22.36 8707.63    18.510544.03   20.91
BR D #Mann= 3
 3481.57     .15 4889.93    .015 5106.69     .15
BC Design=,, 0 ,, 0 ,,,,,,
BC HTab HWMax=23.24

Type RM Length L Ch R = 1 ,23772.84,81.93,80.13,80.12
XS GIS Cut Line= 6
     3196951.318    13785677.202     3196666.048    13785087.646
     3196449.672    13784392.326     3196323.726    13783357.014
     3197297.981    13782012.115     3199191.831    13779722.432
#Sta/Elev= 30
 3481.57   16.52 3630.19    15.4 3686.34   23.15 3820.41   24.04 4113.08   18.16
 4394.02   23.44 4633.96   17.26 4783.64   23.56 4889.93    19.4 4912.75    18.8
 4973.99    4.07 4975.93    -.34 4990.83   -4.78 5010.03    3.66 5033.68    4.76
 5075.95   18.55 5106.69   19.87 5222.97   23.18 5307.57   18.15 5402.07   21.79
 5601.99   17.31 6474.24   20.62 6657.32   15.59 6752.27   21.11 7251.48   18.04
  7390.8   23.01 7607.34    18.1 7765.23   22.36 8707.63    18.510544.03   20.91
#Mann= 3 ,-1 , 0
 3481.57     .15       0 4912.75    .032       0 5106.69     .15       0
#XS Ineff= 2 , 0
         4790.21   22.89 5153.85           22.36
Permanent Ineff=
       F       F
Bank Sta=4889.93,5106.69
XS Rating Curve= 0
Exp/Cntr=0.5,0.3