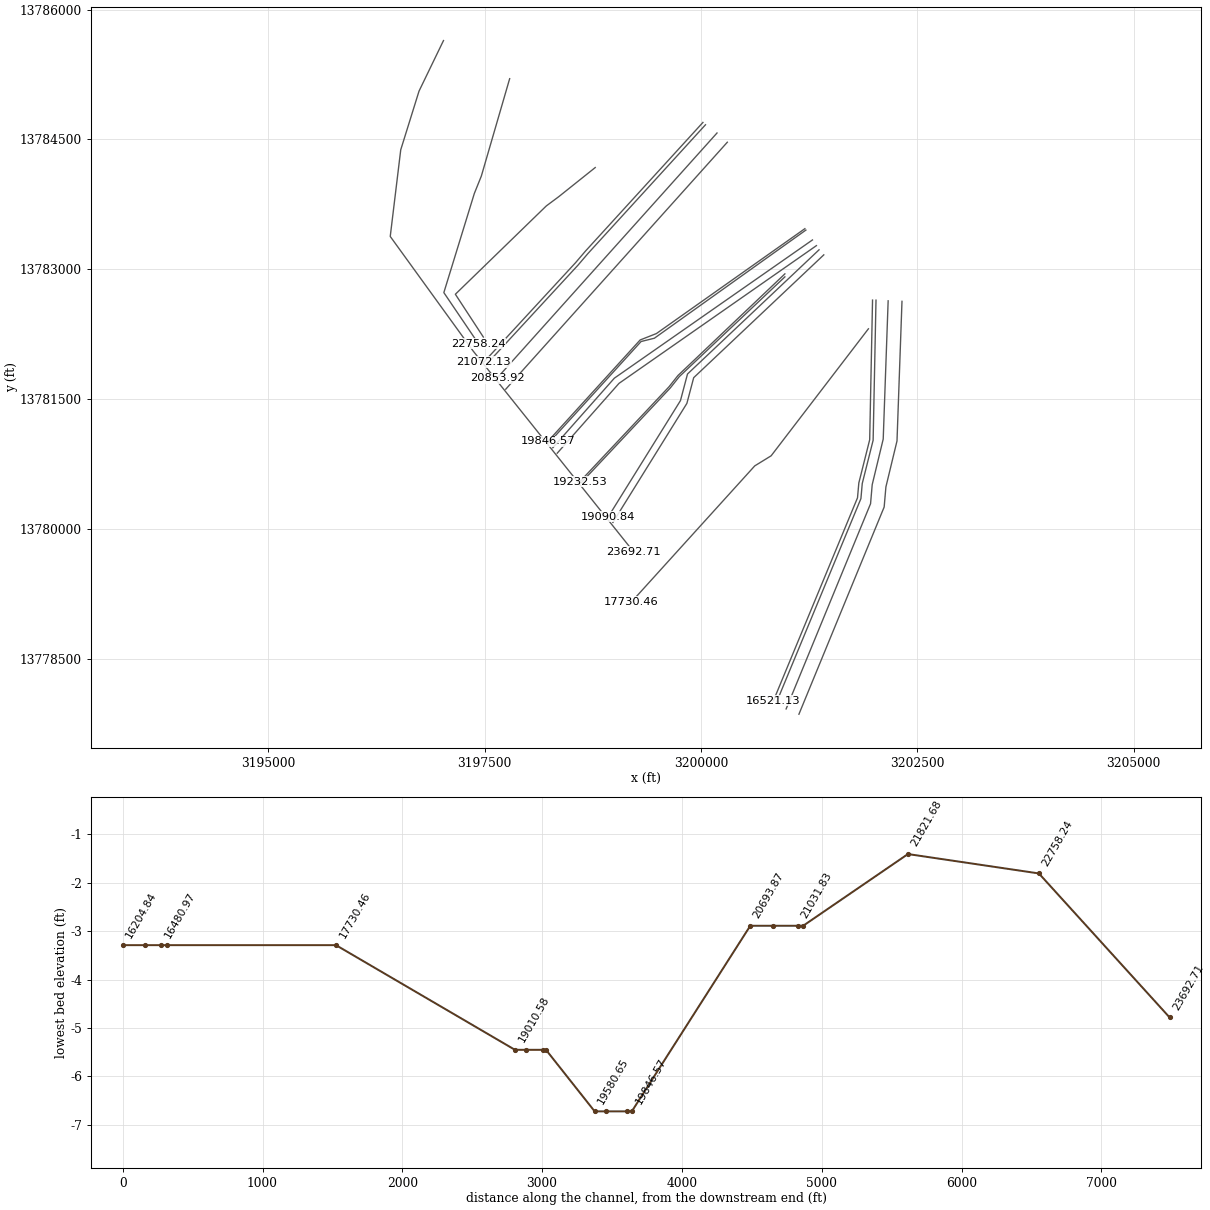
HEC-RAS study B104_00_00.prj: B104-00-00

--- B104_00_00.g01 (geometry) --- (continued)

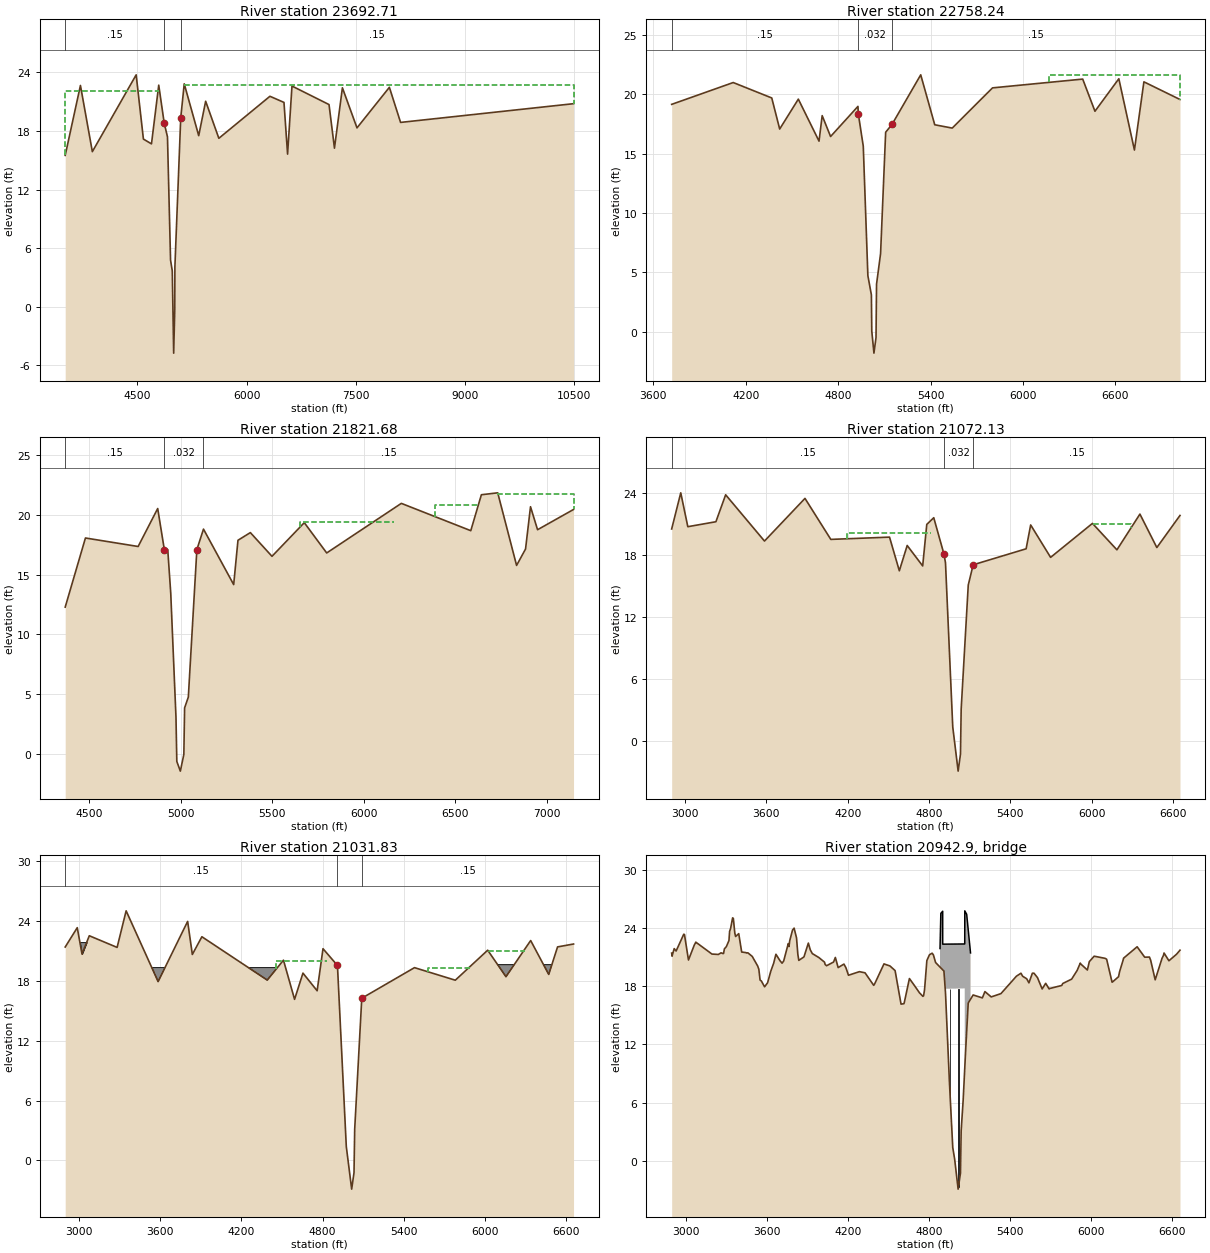
Type RM Length L Ch R = 1 ,23692.71,979.42,934.47,840.59
XS GIS Cut Line= 6
      3197023.33    13785642.357     3196740.498    13785057.838
     3196529.258    13784379.933     3196407.919    13783378.543
     3197366.146    13782054.321     3199221.708    13779732.392
#Sta/Elev= 30
 3509.95    15.5 3719.12   22.67 3882.64   15.88 4484.26   23.76 4583.74   17.17
 4694.53   16.68 4794.14    22.7 4869.45    18.8 4914.05    17.4 4956.32    4.76
 4979.97    3.66 4999.17   -4.78 5014.07    -.34 5016.01    4.07    5096   19.33
 5144.14   22.84 5343.02   17.52 5438.29   21.05 5619.41   17.25 6320.93   21.56
 6513.58   20.93 6563.05   15.63 6623.48   22.61 7132.09   20.71 7206.71   16.24
 7315.83   22.43 7516.09   18.32 7960.79   22.48  8114.4   18.8810489.11    20.8
#Mann= 3 , 0 , 0
 3509.95     .15       0 4869.45    .032       0    5096     .15       0
#XS Ineff= 2 , 0
         4799.53    22.1 5143.11           22.75
Permanent Ineff=
       F       F
Bank Sta=4869.45,5096
XS Rating Curve= 0
Exp/Cntr=0.3,0.1

Type RM Length L Ch R = 1 ,22758.24,1230.44,936.56,648.76
XS GIS Cut Line= 5
     3197788.107    13785201.754      3197460.76    13784076.371
     3197379.513    13783874.564     3197027.389    13782729.422
     3197426.766    13782139.866
#Sta/Elev= 30
 3719.71   19.16 4119.21      21 4369.39    19.7 4420.85   17.08  4541.9    19.6
 4676.25   16.06 4696.71   18.21 4751.26   16.45 4928.92   18.99    4931   18.38
 4963.48   15.63 4993.34    4.72 5016.19     3.1 5018.68     .05 5032.71   -1.81
 5046.18     -.5 5049.59       4  5075.8    6.58 5108.77   16.81 5150.56   17.48
 5336.38   21.65 5427.42   17.44 5540.89   17.16 5802.35   20.55 6387.92   21.29
 6467.45   18.58 6622.45   21.32 6723.65   15.31 6785.06   21.06 7019.44   19.57
#Mann= 3 ,-1 , 0
 3719.71     .15       0 4928.92    .032       0 5150.56     .15       0
#XS Ineff= 2 ,-1
 6170.13 7019.44   21.62 5322.13 5808.41   20.32
Permanent Ineff=
       F       F
#Block Obstruct= 2 , 0
         3896.27   20.07
Bank Sta=4931,5150.56
XS Rating Curve= 0
Exp/Cntr=0.3,0.1

Type RM Length L Ch R = 1 ,21821.68,657.87,749.55,766.2
XS GIS Cut Line= 5
      3198777.04    13784174.785     3198353.942     13783836.98
      3198211.44    13783731.037     3197160.515    13782710.404
      3197483.82    13782215.938
#Sta/Elev= 30
 4370.14   12.28 4480.61   18.05 4768.22   17.34 4875.06   20.51 4911.22   17.08
 4929.89   17.08 4946.28   13.43 4974.85    3.07 4979.36     -.6  4998.6   -1.41
 5017.73    -.02 5021.88    3.87 5042.22    4.77 5088.78   17.08 5124.97   18.79
 5289.77   14.16 5313.21   17.86 5380.81    18.5 5498.86   16.52 5675.19   19.33
 5797.52    16.8 6204.92   20.94 6584.01   18.66 6641.85   21.66 6731.09   21.82
 6834.02   15.76 6882.94   17.13 6910.02   20.66 6948.54   18.74 7144.87   20.43
#Mann= 3 ,-1 , 0
 4370.14     .15       0 4911.22    .032       0 5124.97     .15       0
#XS Ineff= 3 ,-1
 6728.96 7144.87   21.73 6390.21  6631.5   20.83 5653.44 6167.42   19.38
Permanent Ineff=
       F       F       F
#Block Obstruct= 2 , 0
            4875   22.12
Bank Sta=4911.22,5088.78
XS Rating Curve= 0
Exp/Cntr=0.3,0.1

Type RM Length L Ch R = 1 ,21072.13,40.18,40.3,40.14
XS GIS Cut Line= 4
     3200021.701    13784696.221     3198664.215    13783209.295
     3198547.452    13783072.715     3197490.137    13781926.883
#Sta/Elev= 30
 2900.65   20.56 2967.75   24.06 3019.81   20.78 3227.07   21.26 3299.11   23.87
 3585.78   19.39 3884.66   23.52 4075.32   19.55 4508.71   19.77 4581.13   16.51
 4639.12   18.96 4753.43   16.98 4783.66      21 4835.22   21.65  4910.1   18.15
 4921.81   17.29 4975.44    1.39  5015.2   -2.89 5032.49   -1.24 5037.56    3.11
  5089.9   15.13    5126   17.09 5516.98   18.64 5550.58   20.95 5697.69   17.81
 6006.74    21.1  6187.2   18.54 6357.04      22 6481.91   18.76 6652.84   21.87
#Mann= 3 , 0 , 0
 2900.65     .15       0  4910.1    .032       0    5126     .15       0
#XS Ineff= 4 ,-1
 3421.91 3888.11   21.66 6335.66 6652.84   21.48 6007.61 6293.16   21.08
 4191.14 4814.69   20.16
Permanent Ineff=
       F       F       F       F
#Block Obstruct= 2 , 0
         3287.88   22.18  6067.6           19.63
Bank Sta=4910.1,5126
XS Rating Curve= 0
Exp/Cntr=0.5,0.3

Type RM Length L Ch R = 1 ,21031.83,177.15,177.91,182.04
XS GIS Cut Line= 4
     3200051.241    13784669.252     3198694.196    13783182.807
     3198577.363    13783046.146     3197515.488    13781895.373
#Sta/Elev= 30
  2897.2    21.4 2986.36   23.34 3021.42   20.69 3075.36   22.53 3280.96   21.36
  3347.7   25.03 3584.15   17.93 3802.45   23.97 3837.15   20.65 3907.76   22.43
 4391.09   18.08  4510.9   20.08 4593.06   16.15 4655.01   18.78 4759.93   17.01
 4803.25   21.23  4910.1   19.55 4975.44    1.39  5015.2   -2.89 5032.49   -1.24
 5037.56    3.11  5089.9   16.26 5479.77   19.33 5781.45   18.07  6020.9   21.08
 6156.02   18.42 6338.65   22.05 6472.18   18.65 6537.51   21.41 6655.57    21.7
#Mann= 3 ,-1 , 0
  2897.2     .15       0  4910.1    .032       0  5089.9     .15       0
#XS Ineff= 5 ,-1
 3350.42 3800.55   22.69 6328.25 6653.74   21.67 6030.47 6293.63      21
 4458.45 4832.41   19.98 5576.83 5891.91   19.27
Permanent Ineff=
       F       F       F       F       F
#Block Obstruct= 3 ,-1
  2897.2 4453.38   19.33 2990.68 3078.09   21.89 6096.74 6655.57   19.63
Bank Sta=4910.1,5089.9
XS Rating Curve= 0
Exp/Cntr=0.5,0.3

Type RM Length L Ch R = 3 ,20942.9 ,,,
BEGIN DESCRIPTION:
Pineloch @ Bay Oaks Blvd.
END DESCRIPTION:
Bridge Culvert--1,0,-1,-1, 0
Deck Dist Width WeirC Skew NumUp NumDn MinLoCord MaxHiCord MaxSubmerge Is_Ogee
60,53,2.6,0, 8, 8, , , 0.95, 0, 0,0,,
 4881.24 4887.28 4901.04 4901.17 5063.99 5064.41 5078.43  5106.8
   21.87   25.49   25.71   22.32   22.34   25.75   25.39   21.42
                       0 17.7214 17.7667       0
 4881.24 4887.28 4901.04 4901.17 5063.99 5064.41 5078.43  5106.8
   21.87   25.49   25.71   22.32   22.34   25.75   25.39   21.42
                       0 17.7214 17.7667       0
Pier Skew, UpSta & Num, DnSta & Num=  ,4956, 4 ,4956, 4 , 3 , 3 , 0 ,,
     1.4     1.4     2.5     2.5
       0   15.27   15.27   17.77
     1.4     1.4     2.5     2.5
       0   15.27   15.27   17.77
Pier Skew, UpSta & Num, DnSta & Num=  ,5017, 4 ,5017, 4 , 3 , 3 , 0 ,,
     1.4     1.4     2.5     2.5
       0   15.27   15.27   17.77
     1.4     1.4     2.5     2.5
       0   15.27   15.27   17.77
BR Coef=-1 , 1 , 0 ,, 0 ,,,0.8,0,2,0,
WSPro=,,,, 1 ,,,, 0 ,,,, 0 ,,,,-1 ,-1 ,-1 , 0 , 0 , 0 , 0 , 0
BR U #Sta/Elev= 150
  2897.2    21.4 2899.98   21.08 2915.89   21.86 2929.98   21.61 2986.36   23.34
 2988.89   23.32 2991.74   23.31 3021.42   20.69 3065.31   22.26 3072.01   22.41
 3075.36   22.53 3195.19    21.3 3241.83   21.26 3262.72   21.43 3274.04   21.36
 3280.96   21.36 3286.86   21.83 3301.73   22.07 3320.89    22.7 3325.45   23.63
 3332.87   23.93  3347.7   25.03 3353.18   24.97 3364.02   23.46 3369.95   23.11
 3393.04    23.4 3414.11   21.52 3414.27   21.51 3414.84   21.51 3446.12   21.45
 3450.53   21.41 3460.53   21.43 3492.78   21.06 3532.75   20.08 3541.68   19.74
 3550.89   18.62 3560.38   18.53 3584.15   17.93 3606.52   18.35 3629.66   19.52
 3651.29   20.36 3668.05   21.28 3697.96   20.62 3713.43   20.36 3725.39   20.59
 3759.32   22.38 3764.65   22.08  3770.4   22.69 3790.74   23.77 3802.45   23.97
 3820.33   22.96 3830.05   21.28 3837.15   20.65 3875.39   21.01 3907.76   22.43
 3921.89   21.74 3937.16   21.35 3985.69   20.94 4027.17   20.47 4031.85   20.23
 4042.63    20.1 4094.17   20.48 4107.43   20.95  4128.1   19.91 4170.86   20.27
 4185.93   19.88 4204.35   19.12 4285.45   19.49 4326.92   19.37 4391.09   18.08
 4398.54   18.25 4466.96   20.29 4486.65   20.19  4510.9   20.08 4549.07    19.6
 4592.14   16.24 4593.06   16.15 4613.51   16.19 4614.06   16.19 4617.08   16.31
 4655.01   18.78  4693.7   18.03 4729.12   17.32 4754.63   16.95 4759.93   17.01
 4767.02   17.65 4783.94   20.63 4803.25   21.23 4823.06   21.39 4832.47   21.21
 4848.52   20.43  4910.1   19.55 4921.81   17.29 4951.23    8.02 4975.44    1.39
 4989.56     .19  5015.2   -2.89 5032.49   -1.24 5037.56    3.11 5052.25    6.23
 5070.23   11.23  5089.9   16.26    5126   17.09 5194.42   16.79 5213.35   17.44
 5259.74   16.89 5331.66   17.23 5445.98   19.02 5479.77   19.33 5492.02   19.02
 5521.95   18.76 5538.77   18.34 5564.12   19.33 5576.14   19.33 5601.74   18.88
 5636.49   17.71 5662.52   18.29 5686.62   17.74 5686.74   17.75 5687.72   17.74
 5781.45   18.07 5788.64   18.27 5854.44   18.72 5894.87   19.61 5918.32   20.37
 5922.58   20.27 5970.79   19.66 5985.13   20.52  6020.9   21.08 6101.95   20.86
 6113.18   20.77 6148.53   18.71 6153.24   18.41 6156.02   18.42 6201.25   18.97
 6208.96   19.49 6235.91   20.72 6238.31   20.88 6239.44   20.89 6338.65   22.05
 6394.55   20.98 6429.72   20.99 6438.78   20.66 6472.18   18.65 6522.68   20.86
 6533.78   21.18 6537.51   21.41 6573.67   20.61 6629.78   21.28 6655.57    21.7
BR U #Mann= 3
  2897.2     .15  4910.1    .015  5089.9     .15
BR D #Sta/Elev= 155
 2872.94   24.45 2895.32   23.88 2954.86   24.18 3020.09   23.21 3039.44   23.44
 3070.25   23.85 3145.12   21.33 3160.53   20.79 3169.72   20.54 3247.22   21.88
 3294.27   22.19 3325.14   22.74 3338.66   22.63 3373.15   22.17 3376.16   21.95
 3381.59   21.94 3434.86   21.96 3451.46   21.62 3500.27   21.61 3504.68   21.62
 3510.17   21.71  3516.5   22.01 3532.52   22.65 3546.23   23.06 3563.97   22.29
 3580.49   18.84 3594.53   17.21 3598.74   16.85 3618.35   16.84 3656.37   16.86
 3670.15   16.82 3675.26   16.81 3681.24    16.8 3686.22    16.8  3721.7   18.07
 3738.91   20.66    3782   21.48 3795.91   21.89 3805.85   22.24 3841.11   22.21
 3841.61   22.24 3842.46   22.18 3856.34   21.27    3869   21.29 3914.03   21.24
 3945.68   22.21 3957.44    23.1 4039.91   23.53 4050.05   23.25  4060.4   23.23
 4068.58   23.49 4156.08   21.48 4160.72   21.24 4177.99   21.41 4213.83   21.22
 4235.73    20.1 4250.77   19.62 4256.32   19.57  4285.8   21.02 4303.82   19.66
 4311.71   19.66 4409.51   20.37 4426.01   20.48    4427   20.48 4437.62   20.39
 4532.11   19.57 4537.94   19.56 4579.12   20.43 4587.58   20.34 4621.24   19.79
 4648.53   19.38 4695.36   19.55  4740.1   18.62 4758.46   19.02 4790.41   20.99
 4813.38   21.23 4864.69    21.2    4867   20.43    4872   19.55    4888   17.29
 4951.23   11.18 4975.44    1.39 4989.56     .19  5015.2   -2.89 5032.49   -1.24
 5037.56    3.11 5052.25    6.23 5070.23   11.23  5089.9   17.35    5094   18.62
 5114.31   21.06 5121.96   21.42 5129.01   21.49 5140.49   21.18 5159.21   20.91
 5166.88   19.98 5180.45    16.5 5189.34   15.65 5191.07   15.67  5211.8   16.51
 5226.39   17.39 5250.26   16.79 5293.39   17.15 5328.19   17.61 5336.05   17.84
 5339.78   17.68  5362.8   21.19 5370.81   22.32    5374   22.59 5382.27   22.81
  5391.5   22.99  5392.9      23 5394.15    22.8 5414.14   20.44 5434.45   19.67
 5446.01   19.21 5458.89    18.2 5511.58    17.4 5537.61    18.5 5567.37   18.82
 5618.69   18.62 5638.77   18.87 5700.71   19.53 5720.25   19.45 5766.51   19.56
  5789.1   20.14 5853.11   19.95 5860.27    19.9 5927.28   20.55  5958.4   19.85
 6000.85   20.04 6075.55   20.66 6112.29   21.14 6129.83   20.46 6166.03   18.74
 6219.42   20.65 6221.06    20.7  6224.4   20.76  6255.3   22.12 6297.83   22.42
    6344   21.84 6374.39   20.74 6447.92    19.3    6465   19.21 6469.68   19.52
  6497.6   21.42 6512.94   21.76 6534.23   21.09 6559.18   20.86 6574.85   20.72
 6595.35   21.82 6617.54   21.51 6639.33   21.44 6656.93    21.3 6681.47   21.44
BR D #Mann= 3
 2872.94     .15 4864.69    .015 5114.31     .15
BC Design=,, 0 ,, 0 ,,,,,,
BC HTab HWMax=24.96

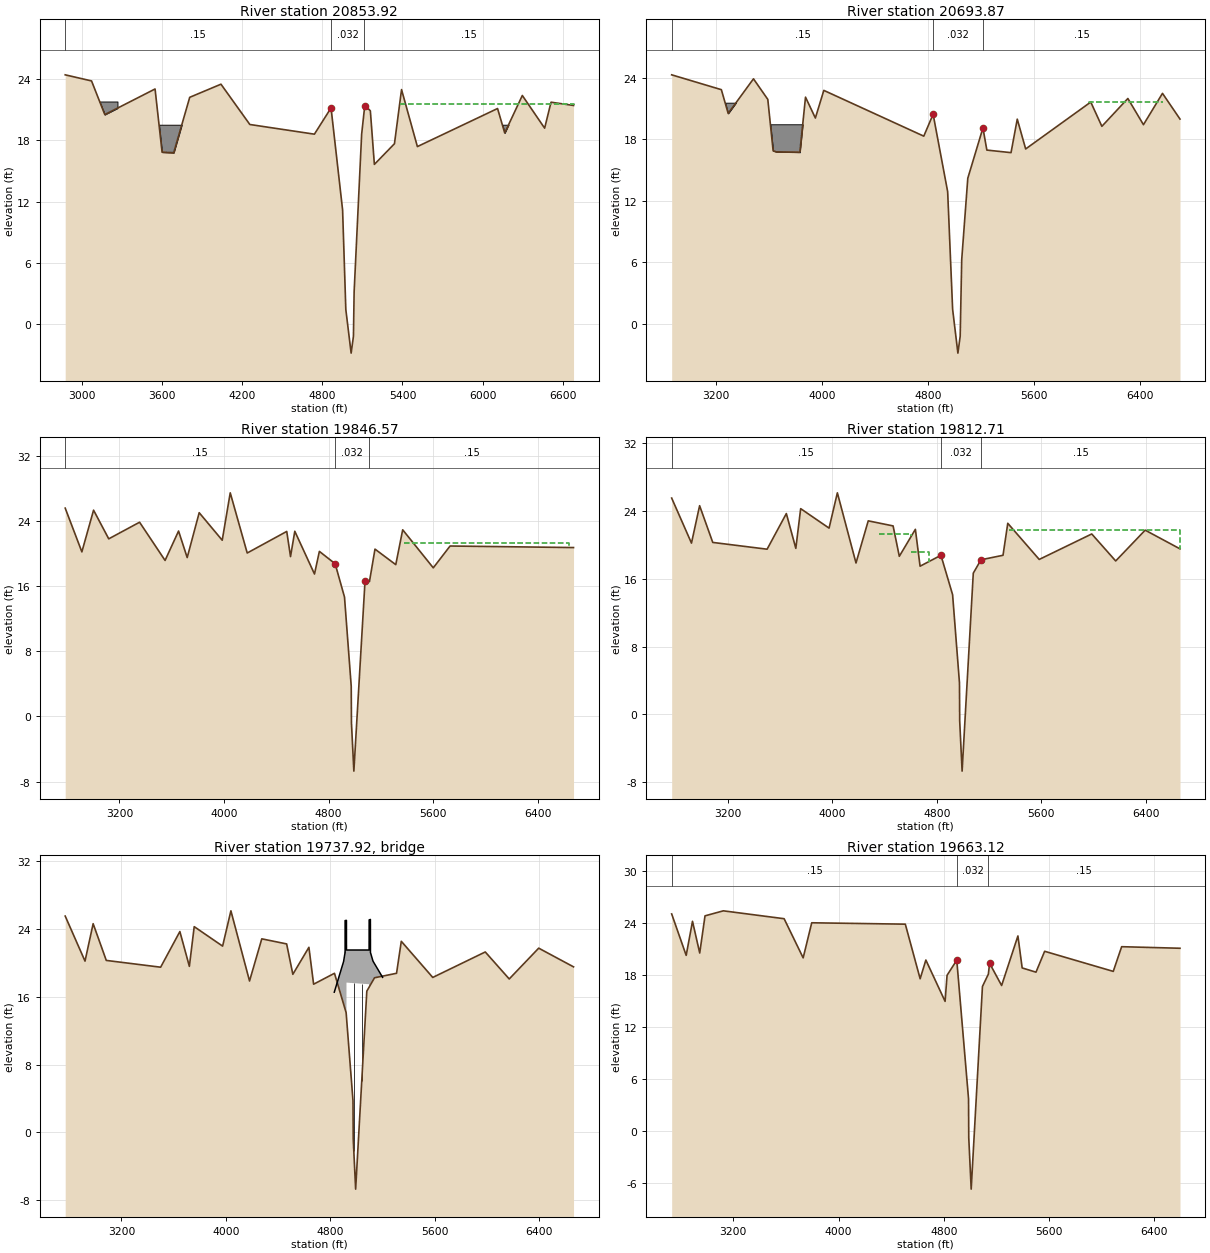
Type RM Length L Ch R = 1 ,20853.92,160.04,160.05,160.06
XS GIS Cut Line= 2
     3200184.367    13784574.162     3197641.072    13781739.279
#Sta/Elev= 30
 2872.94   24.45 3070.25   23.85 3169.72   20.54 3546.23   23.06 3598.74   16.85
 3686.22    16.8 3805.85   22.24 4039.91   23.53 4256.32   19.57  4740.1   18.62
 4864.69    21.2 4951.23   11.18 4975.44    1.39  5015.2   -2.89 5032.49   -1.24
 5037.56    3.11    5094   18.62 5114.31   21.06 5121.96   21.42 5159.21   20.91
 5189.34   15.65 5339.78   17.68  5392.9      23 5511.58    17.4 6112.29   21.14
 6166.03   18.74 6297.83   22.42    6465   19.21 6512.94   21.76 6681.47   21.44
#Mann= 3 ,-1 , 0
 2872.94     .15       0 4864.69    .032       0 5114.31     .15       0
#XS Ineff= 2 ,-1
 5379.95 6681.47   21.57  3537.4 3821.33    21.5
Permanent Ineff=
       F       F
#Block Obstruct= 3 ,-1
  3101.4 3264.57   21.83 3544.29 3777.39   19.55 6114.22 6213.29   19.55
Bank Sta=4864.69,5121.96
XS Rating Curve= 0
Exp/Cntr=0.5,0.3

Type RM Length L Ch R = 1 ,20693.87,976.4,847.3,829.13
XS GIS Cut Line= 2
     3200303.463    13784467.316       3197742.7    13781612.962
#Sta/Elev= 30
    2866   24.29 3240.79   22.84 3292.33   20.52 3483.13    23.9 3591.22   21.89
 3631.35   16.87 3655.28   16.77 3833.12   16.73 3875.66   22.11 3950.01   20.07
 4013.75   22.77 4767.92    18.3 4838.28   20.44    4948   12.88 4985.44    1.39
  5025.2   -2.89 5042.49   -1.24    5054    6.23  5099.9   14.19 5214.05    19.1
 5243.66   16.94 5425.99   16.69 5473.06   19.96 5536.47   17.05 6027.51   21.63
 6111.33   19.26  6307.4   21.98 6424.98   19.42  6568.6   22.48 6700.69   19.97
#Mann= 3 ,-1 , 0
    2866     .15       0 4838.28    .032       0 5214.05     .15       0
#XS Ineff= 3 ,-1
 6016.62 6570.64   21.65 3578.95 3897.51    21.5 5473.19 5892.77   19.63
Permanent Ineff=
       F       F       F
#Block Obstruct= 2 ,-1
    2866 3870.63   19.46 3235.43 3369.46   21.57
Bank Sta=4838.28,5214.05
XS Rating Curve= 0
Exp/Cntr=0.3,0.1

Type RM Length L Ch R = 1 ,19846.57,29.45,33.86,22.82
XS GIS Cut Line= 4
     3201199.716    13783468.382     3199483.756    13782256.035
     3199296.107    13782182.119     3198228.702    13781008.892
#Sta/Elev= 30
 2785.31   25.57 2912.82    20.2 3002.29   25.32 3118.37    21.8 3354.28   23.84
 3549.37   19.15 3652.56   22.76 3718.57    19.5  3810.4   25.01 3986.55   21.63
 4047.86   27.45 4177.72   20.06  4480.1   22.71 4509.06   19.62 4541.79   22.73
 4692.46   17.48 4729.81   20.26  4850.5   18.74    4922   14.65 4973.45     3.7
 4975.13    -.79 4993.62   -6.72 5079.23   16.67 5112.94   16.55 5155.24   20.54
 5314.25   18.63 5367.22   22.91 5601.18   18.24 5729.67   20.92 6674.15   20.73
#Mann= 3 ,-1 , 0
 2785.31     .15       0  4850.5    .032       0 5112.94     .15       0
#XS Ineff= 1 ,-1
 5374.13 6638.69   21.32
Permanent Ineff=
       F
#Block Obstruct= 2 , 0
         4237.76   21.55
Bank Sta=4850.5,5079.23
XS Rating Curve= 0
Exp/Cntr=0.5,0.3

Type RM Length L Ch R = 1 ,19812.71,126.14,149.59,63.63
XS GIS Cut Line= 4
     3201211.336    13783452.104     3199460.607    13782202.348
     3199306.816    13782164.171     3198241.392     13780993.12
#Sta/Elev= 30
  2769.5   25.54  2921.2   20.22 2983.45   24.64 3084.12    20.3 3500.31    19.5
 3647.64   23.71 3720.27    19.6 3757.39   24.29  3974.8   21.99 4038.42   26.16
 4181.02   17.87 4274.84   22.85 4465.17   22.25 4512.75   18.66 4635.74   21.85
 4671.74   17.49 4831.53   18.78 4920.77   14.13 4973.45     3.7 4975.13    -.79
 4993.62   -6.72 5079.23   16.67  5138.3   18.25 5306.89   18.78 5343.28   22.56
 5584.18   18.29 5986.33    21.3 6169.82   18.11  6395.5   21.75 6662.18   19.54
#Mann= 3 ,-1 , 0
  2769.5     .15       0 4831.53    .032       0  5138.3     .15       0
#XS Ineff= 3 ,-1
 5350.82 6662.18   21.79 4360.14  4604.9   21.32  4604.9 4738.93   19.21
Permanent Ineff=
       F       F       F
#Block Obstruct= 2 , 0
         4214.45   21.55
Bank Sta=4831.53,5138.3
XS Rating Curve= 0
Exp/Cntr=0.5,0.3

Type RM Length L Ch R = 3 ,19737.92,,,
BEGIN DESCRIPTION:
Concrete Footbridge on Golf Course
END DESCRIPTION:
Bridge Culvert--1,0,-1,-1, 0
Deck Dist Width WeirC Skew NumUp NumDn MinLoCord MaxHiCord MaxSubmerge Is_Ogee
88,12,2.6,0, 14, 14, , , 0.95, 0, 0,0,,
    4830 4901.27 4912.57 4912.87 4912.88 4923.17 4923.42 5096.64 5096.99 5106.66
 5106.67 5107.05 5126.38    5200
   16.55   20.17   21.24   21.24   25.01   25.03   21.53   21.53   25.09   25.14
   25.14   21.24   20.22    18.3
                                                   17.68   17.49
                                
    4830 4901.27 4912.57 4912.87 4912.88 4923.17 4923.42 5096.64 5096.99 5106.66
 5106.67 5107.05 5126.38    5200
   16.55   20.17   21.24   21.24   25.01   25.03   21.53   21.53   25.09   25.14
   25.14   21.24   20.22    18.3
                                                   17.68   17.49
                                
Pier Skew, UpSta & Num, DnSta & Num=  ,4979.708, 4 ,4979.708, 4 , 3 , 3 , 0 ,,
     1.7     1.7     2.8     2.8
      -6   14.98   14.98 17.7854
     1.7     1.7     2.8     2.8
      -6   14.98   14.98 17.7854
Pier Skew, UpSta & Num, DnSta & Num=  ,5040.32, 4 ,5040.32, 4 , 3 , 3 , 0 ,,
     1.7     1.7     2.8     2.8
      -6   14.98   14.98   17.79
     1.7     1.7     2.8     2.8
      -6   14.98   14.98   17.79
BR Coef=-1 , 1 , 0 ,, 0 ,,,0.8,0,2,0,
WSPro=,,,, 1 ,,,, 0 ,,,, 0 ,,,,-1 ,-1 ,-1 , 0 , 0 , 0 , 0 , 0
BC Design=,, 0 ,, 0 ,,,,,,
BC HTab HWMax=25.77

Type RM Length L Ch R = 1 ,19663.12,88.65,82.47,83.4
XS GIS Cut Line= 3
     3201287.407    13783337.996     3198998.018    13781740.635
     3198286.829    13780936.644
#Sta/Elev= 30
 2731.27   25.04 2841.62   20.26 2889.67   24.19 2944.54   20.53 2984.79   24.82
 3124.01    25.4 3586.25   24.49 3731.03   19.97 3796.21   24.02 4507.74   23.86
  4620.5   17.56    4664   19.72 4810.15   14.95 4825.19   17.96 4899.18   19.71
  4901.6   19.24 4988.45     3.7 4990.13    -.79 5008.62   -6.72 5094.23   16.67
 5139.38    18.1 5148.39   19.35 5239.97   16.78 5363.86    22.5 5396.18   18.81
  5501.3   18.32 5567.08   20.73 6088.76   18.41 6152.66   21.26 6596.24   21.08
#Mann= 3 ,-1 , 0
 2731.27     .15       0  4901.6    .032       0 5139.38     .15       0
#XS Ineff= 2 ,-1
 5362.47 6481.35   20.85 4569.93 4884.62   18.97
Permanent Ineff=
       F       F
#Block Obstruct= 2 , 0
         3789.04   22.49
Bank Sta=4899.18,5148.39
XS Rating Curve= 0
Exp/Cntr=0.5,0.3

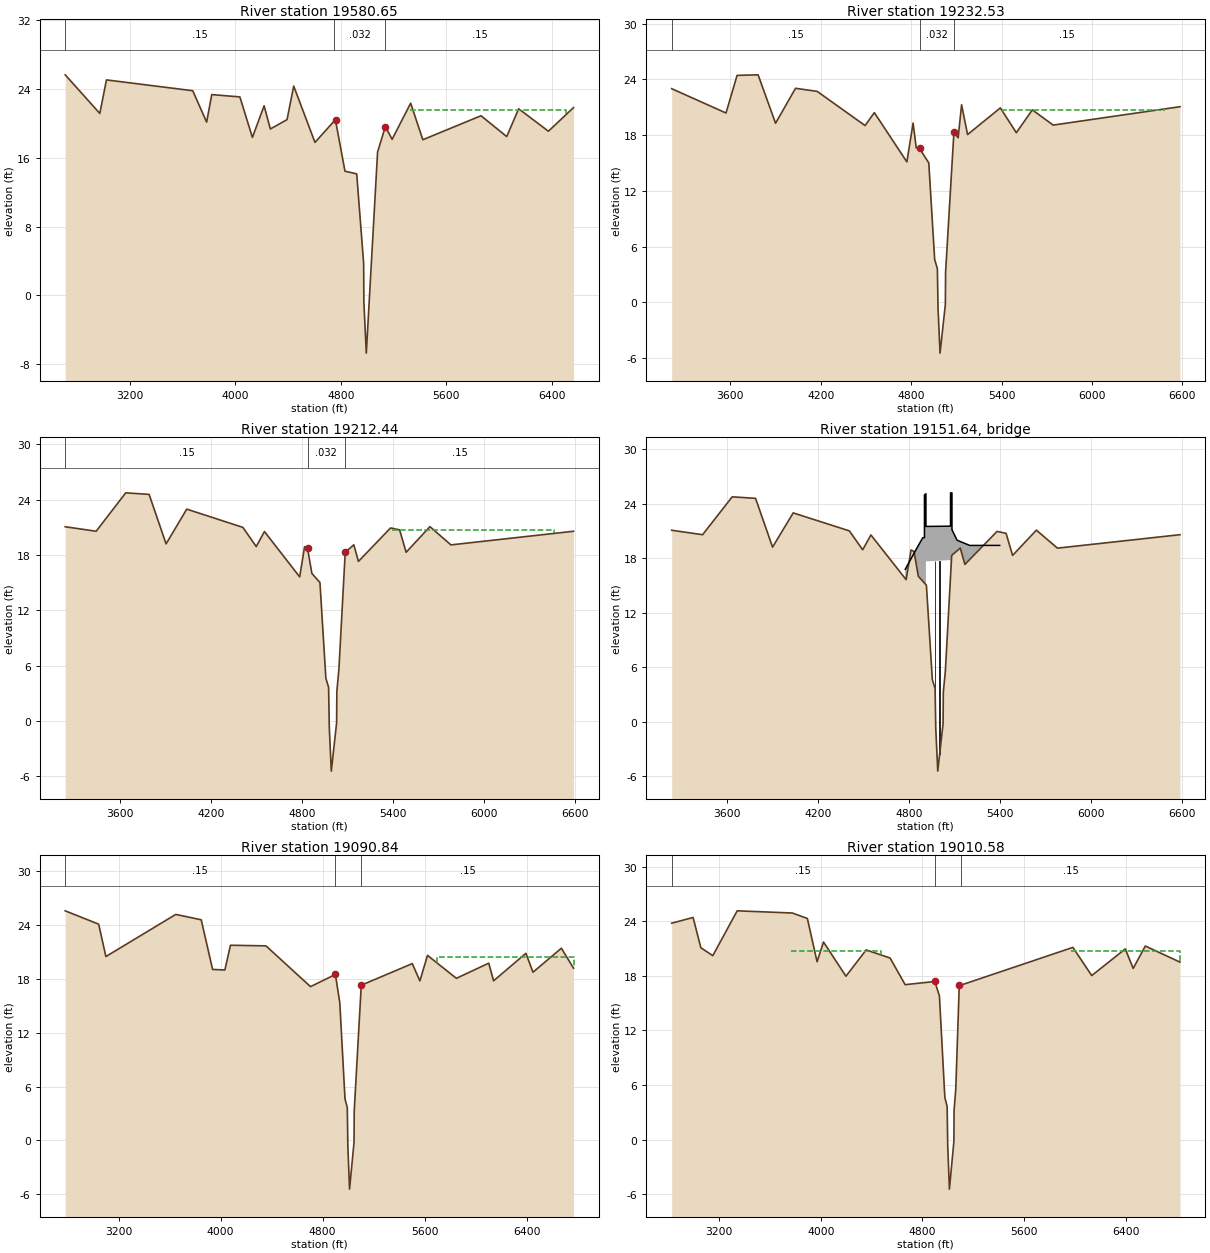
Type RM Length L Ch R = 1 ,19580.65,297.38,348.12,454.74
XS GIS Cut Line= 3
     3201333.184    13783272.387     3199051.618    13781680.485
     3198337.702    13780873.411
#Sta/Elev= 30
 2707.43   25.65 2970.15   21.16 3020.73   25.06 3675.79    23.8 3781.29   20.15
 3820.15   23.35 4033.69   23.08 4128.81   18.37 4217.65   22.05 4265.11   19.35
 4391.83   20.44 4442.36   24.34 4603.96   17.79 4750.68   20.29 4760.04   20.34
 4831.71   14.44 4920.77   14.13 4973.45     3.7 4975.13    -.79 4993.62   -6.72
 5079.23   16.67 5138.28   19.63 5189.64   18.15 5330.45   22.35 5422.74    18.1
  5864.4   20.89 6059.76   18.47 6150.57    21.7 6376.21   19.09 6566.98   21.84
#Mann= 3 ,-1 , 0
 2707.43     .15       0 4750.68    .032       0 5138.28     .15       0
#XS Ineff= 3 ,-1
 3666.67 4453.38   22.73 5327.51 6510.49   21.55 4552.45 4756.41   19.09
Permanent Ineff=
       F       F       F
Bank Sta=4760.04,5138.28
XS Rating Curve= 0
Exp/Cntr=0.3,0.1

Type RM Length L Ch R = 1 ,19232.53,27.32,20.09,20.29
XS GIS Cut Line= 4
      3200968.86    13782945.901     3199733.455     13781771.66
     3199629.406    13781640.586      3198600.83    13780546.361
#Sta/Elev= 30
 3210.34   23.01 3570.95   20.39 3644.46   24.44 3783.98    24.5 3899.82   19.29
 4032.27   23.05 4176.06   22.72 4493.98   19.04 4555.36   20.43 4771.22   15.13
 4812.61   19.31  4833.3   16.64 4855.49   16.63 4857.14   16.53 4916.63   15.02
 4955.74    4.63 4973.71    3.64 4978.22    -.67 4991.45   -5.45 5026.64    -.21
 5028.12    3.23 5083.37    18.3 5111.59   17.73 5134.39   21.28 5174.08   18.07
 5391.68   20.94 5497.63   18.27 5604.01   20.73 5742.08   19.09 6583.88   21.07
#Mann= 3 ,-1 , 0
 3210.34     .15       0 4857.14    .032       0 5083.37     .15       0
#XS Ineff= 2 ,-1
 3806.53  4030.3   21.41 5410.26 6482.52   20.69
Permanent Ineff=
       F       F
Bank Sta=4855.49,5083.37
XS Rating Curve= 0
Exp/Cntr=0.5,0.3

Type RM Length L Ch R = 1 ,19212.44,52.29,121.6,263.58
XS GIS Cut Line= 4
      3200968.86     13782911.39     3199748.221    13781758.093
     3199644.551    13781627.497     3198613.488    13780530.626
#Sta/Elev= 30
 3237.15   21.07 3441.12   20.58 3636.26   24.75 3790.31   24.58 3902.27   19.21
 4038.49   22.98 4408.64      21 4496.48   18.92 4550.77   20.55 4782.98   15.63
 4815.39    18.9  4834.9   18.72 4863.55      16 4916.63   15.02 4955.74    4.63
 4973.71    3.64 4978.22    -.67 4991.45   -5.45 5026.64    -.21 5028.12    3.23
 5041.65    5.59 5083.37    18.3 5139.95   19.11 5170.51   17.31 5382.42   20.94
  5441.9   20.73 5484.95    18.3 5641.72   21.08 5780.41    19.1 6588.59   20.58
#Mann= 3 ,-1 , 0
 3237.15     .15       0  4834.9    .032       0 5083.37     .15       0
#XS Ineff= 2 ,-1
 5391.61 6459.21   20.69 3837.04 4550.33   20.52
Permanent Ineff=
       F       F
Bank Sta=4834.9,5083.37
XS Rating Curve= 0
Exp/Cntr=0.5,0.3

Type RM Length L Ch R = 3 ,19151.64,,,
BEGIN DESCRIPTION:
Concrete Footbridge on Golf Course
END DESCRIPTION:
Bridge Culvert--1,0,-1,-1, 0
Deck Dist Width WeirC Skew NumUp NumDn MinLoCord MaxHiCord MaxSubmerge Is_Ogee
70,14,2.6,0, 15, 15, , , 0.95, 0, 0,0,,
    4777    4846 4892.73 4903.81 4903.82 4913.47 4913.71  5075.5 5075.71  5085.1
 5085.11 5085.19    5119    5202    5400
   16.77   18.87   20.25   20.25   24.97   25.09   21.49   21.52   25.18   25.19
   21.12   21.12   19.97    19.4    19.4
                                                   17.64   17.79
                                        
    4792    4861 4907.73 4918.81 4918.82 4928.47 4928.71  5090.5 5090.71  5100.1
 5100.11 5100.19    5134    5217    5500
   16.77   18.87   20.25   20.25   24.97   25.09   21.49   21.52   25.18   25.19
   21.12   21.12   19.97    19.4    19.4
                                                   17.64   17.79
                                        
Pier Skew, UpSta & Num, DnSta & Num=  ,4975, 4 ,4990, 4 , 3 , 3 , 0 ,,
     1.7     1.7     2.8     2.8
      -6   14.97   14.97   17.77
     1.7     1.7     2.8     2.8
      -6   14.97   14.97   17.77
Pier Skew, UpSta & Num, DnSta & Num=  ,5004, 4 ,5019, 4 , 3 , 3 , 0 ,,
     1.7     1.7     2.8     2.8
      -6   14.97   14.97   17.77
     1.7     1.7     2.8     2.8
      -6   14.97   14.97   17.77
BR Coef=-1 , 1 , 0 ,, 0 ,,,0.8,0,2,0,
WSPro=,,,, 1 ,,,, 0 ,,,, 0 ,,,,-1 ,-1 ,-1 , 0 , 0 , 0 , 0 , 0
BC Design=,, 0 ,, 0 ,,,,,,
BC HTab HWMax=24.76

Type RM Length L Ch R = 1 ,19090.84,95.62,80.26,81.95
XS GIS Cut Line= 4
     3201363.479    13783223.888     3199843.424    13781788.837
      3199761.85     13781481.08      3198928.08    13780139.609
#Sta/Elev= 30
 2780.52    25.6 3043.16   24.11 3099.73    20.5 3648.09    25.2 3847.68    24.6
 3937.01   19.06 4033.33      19 4077.16   21.76 4355.78   21.69 4705.39   17.14
 4894.31   18.46 4900.01   18.54    4935   15.35 4975.74    4.63 4993.71    3.64
 4998.22    -.67 5011.45   -5.45 5046.64    -.21 5048.12    3.23 5103.37    17.3
  5503.7   19.71 5563.26   17.78 5623.09   20.63 5849.73   18.07 6103.71   19.76
 6141.38   17.79 6395.12   20.86 6450.62   18.75 6673.61   21.43 6768.81    19.2
#Mann= 3 ,-1 , 0
 2780.52     .15       0 4894.31    .032       0 5103.37     .15       0
#XS Ineff= 2 ,-1
 3853.15 4092.07   21.44 5700.47 6768.81    20.5
Permanent Ineff=
       F       F
Bank Sta=4900.01,5103.37
XS Rating Curve= 0
Exp/Cntr=0.5,0.3

Type RM Length L Ch R = 1 ,19010.58,1252.15,1280.12,1140.52
XS GIS Cut Line= 4
     3201418.398    13783165.717     3199914.915    13781746.311
     3199836.113    13781449.014      3198981.22    13780073.559
#Sta/Elev= 30
 2828.89   23.79 2997.28   24.42 3058.17   21.09 3152.06   20.22 3343.74   25.15
 3776.85   24.91 3895.21   24.31 3971.57   19.55 4022.17   21.72 4198.49   17.96
  4357.2   20.85 4545.56   19.96 4663.67   17.03 4896.54   17.38    4933    15.8
 4975.74    4.63 4993.71    3.64 4998.22    -.67 5011.45   -5.45 5046.64    -.21
 5048.12    3.23 5061.65    5.59    5089      17    5106      17 5981.84   21.13
 6130.05   18.03 6393.52   20.96 6455.92   18.82 6551.13   21.28 6823.58   19.51
#Mann= 3 ,-1 , 0
 2828.89     .15       0 4896.54    .032       0    5106     .15       0
#XS Ineff= 2 ,-1
 3765.73 4470.86   20.73 5968.53 6823.58   20.73
Permanent Ineff=
       F       F
Bank Sta=4896.54,5089
XS Rating Curve= 0
Exp/Cntr=0.3,0.1

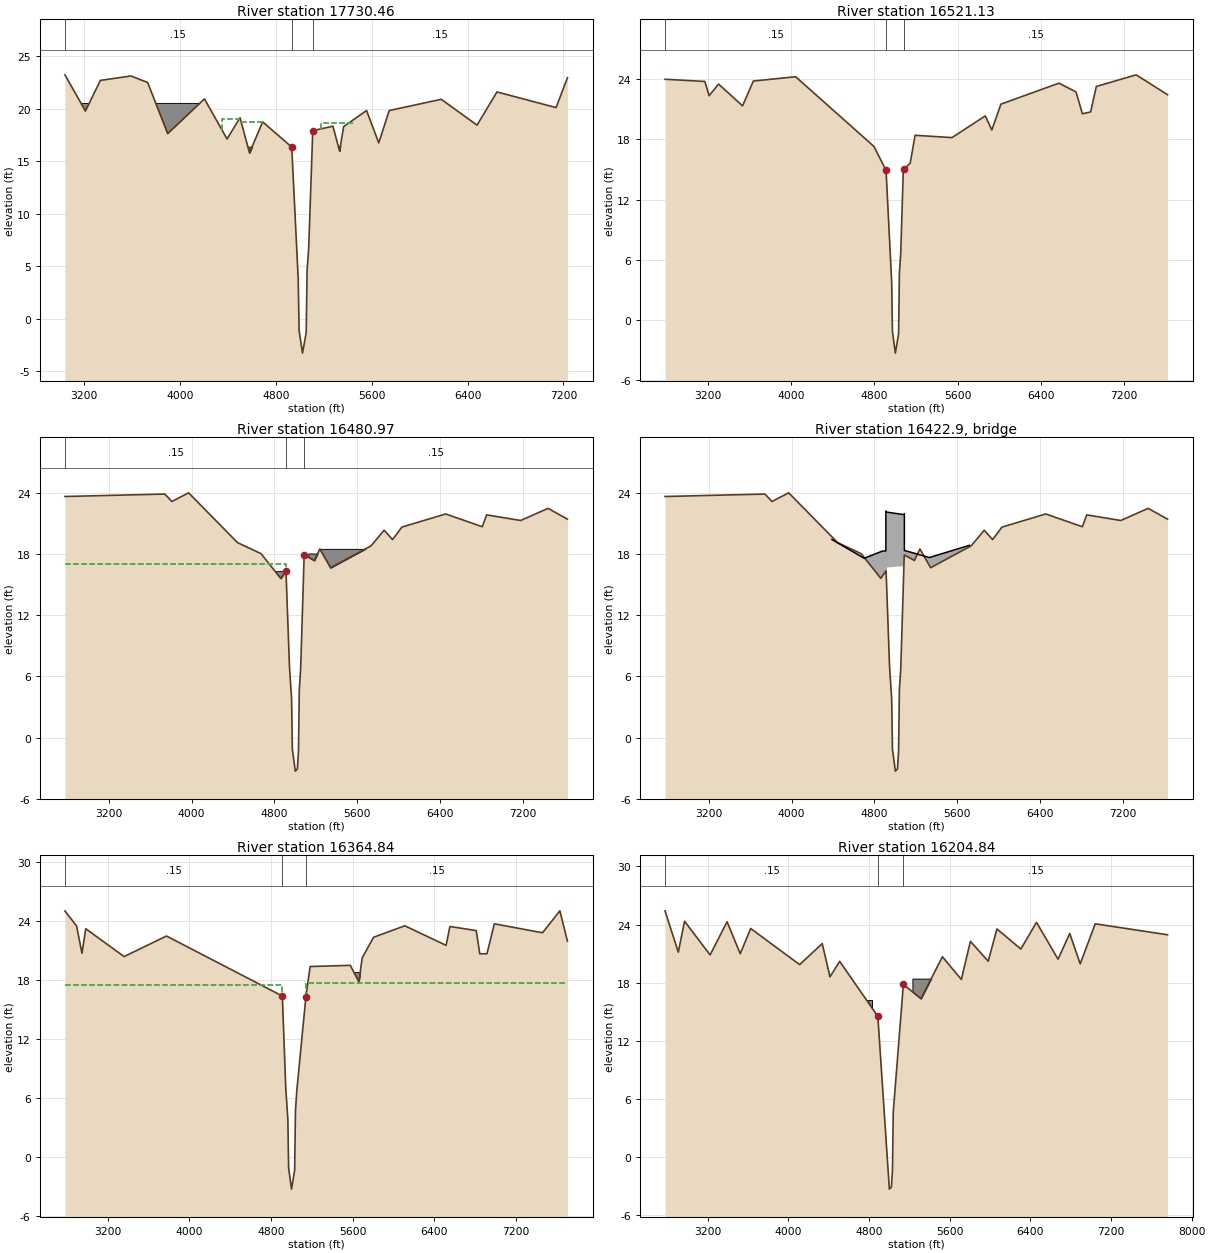
Type RM Length L Ch R = 1 ,17730.46,912.28,1209.33,1421.29
XS GIS Cut Line= 4
     3201934.017    13782311.027     3200809.979    13780843.481
     3200620.498    13780726.862     3199195.434     13779154.05
#Sta/Elev= 30
 3039.57   23.21 3210.89   19.76 3335.43   22.68 3590.68    23.1 3729.93   22.48
 3897.47   17.61 4203.78   20.92 4392.72    17.1 4500.83   19.12 4579.92   15.78
 4689.72   18.73 4932.26   16.33 4986.26     3.8 4993.74   -1.14 5022.03   -3.29
 5052.89   -1.35 5060.62    4.64  5073.7     6.7 5107.74   17.89 5276.08   18.32
  5331.5   15.95 5365.45   18.28 5556.71   19.81 5658.38   16.73 5745.72   19.81
 6180.05   20.88 6478.55   18.42 6645.05   21.58  7138.1   20.09 7233.01   22.93
#Mann= 3 ,-1 , 0
 3039.57     .15       0 4932.26    .032       0 5107.74     .15       0
#XS Ineff= 5 ,-1
 5942.08 6711.31   20.24 5556.53  5786.1   19.76 4350.67 4497.69   18.96
 4507.18 4688.97   18.75 5174.08 5456.79   18.61
Permanent Ineff=
       F       F       F       F       F
#Block Obstruct= 3 ,-1
 3039.57 4194.33   20.49 4241.15 4672.99   16.37 5221.55 5457.73   16.45
Bank Sta=4932.26,5107.74
XS Rating Curve= 0
Exp/Cntr=0.3,0.1

Type RM Length L Ch R = 1 ,16521.13,40.7,40.16,41.08
XS GIS Cut Line= 5
     3201981.843    13782643.006     3201948.786    13781028.724
     3201823.383    13780529.895     3201808.134    13780358.061
     3200837.153    13778014.944
#Sta/Elev= 30
 2784.28   23.98 3167.71   23.76 3209.03   22.34 3299.69    23.5  3530.9   21.33
 3634.41    23.8 4041.95   24.23 4795.61   17.29 4912.26   14.91 4966.26     3.8
 4973.74   -1.14 5002.03   -3.29 5032.89   -1.35 5040.62    4.64  5053.7     6.7
 5077.16   14.59 5087.74      15 5145.11   15.65 5191.74    18.4  5546.9   18.17
 5867.47   20.33 5930.35   18.93 6018.07    21.5 6576.55   23.59  6740.8   22.72
 6802.51   20.54 6882.02   20.73 6936.39   23.26 7319.94   24.42  7622.1   22.44
#Mann= 3 ,-1 , 0
 2784.28     .15       0 4912.26    .032       0 5087.74     .15       0
Bank Sta=4912.26,5087.74
XS Rating Curve= 0
Exp/Cntr=0.5,0.3

Type RM Length L Ch R = 1 ,16480.97,112.23,116.13,134.01
XS GIS Cut Line= 5
     3202021.834    13782642.187     3201988.684     13781023.37
     3201862.947     13780523.21     3201847.435    13780348.415
     3200874.105    13777999.631
#Sta/Elev= 30
  2777.4   23.61 3742.61   23.85 3810.09   23.12 3971.74   23.97 4444.56   19.09
 4671.45   18.01 4861.36   15.59 4912.26   16.33 4946.01     6.9 4966.26     3.8
 4973.74   -1.14 5002.03   -3.29 5022.14   -3.07 5032.89   -1.35 5040.62    4.64
  5053.7     6.7 5087.74   17.89 5186.22   17.34  5238.9   18.47  5342.5   16.63
 5734.11   18.78  5859.9   20.31 5941.32   19.39 6030.79   20.61 6454.12    21.9
  6807.8   20.65 6849.87   21.81 7178.83   21.26  7442.8   22.45 7630.23   21.39
#Mann= 3 ,-1 , 0
  2777.4     .15       0 4912.26    .032       0 5087.74     .15       0
#XS Ineff= 2 , 0
       0 4912.26      17 5087.74       0    17.6
Permanent Ineff=
       F       F
#Block Obstruct= 3 ,-1
 4792.14 4910.85    16.3 5127.55  5229.2   18.03 5238.44  5732.8   18.48
Bank Sta=4912.26,5087.74
XS Rating Curve= 0
Exp/Cntr=0.5,0.3

Type RM Length L Ch R = 3 ,16422.9 ,,,
BEGIN DESCRIPTION:
Eldorado
END DESCRIPTION:
Bridge Culvert--1,0,-1,-1, 0
Deck Dist Width WeirC Skew NumUp NumDn MinLoCord MaxHiCord MaxSubmerge Is_Ogee
37,38,2.6,0, 14, 14, , , 0.95, 0, 0,0,,
    4389    4700 4878.05 4910.14 4910.15 4919.64 4919.64 5080.03 5080.03 5088.82
 5088.83 5100.07    5330    5717
    19.4   17.56   18.27   18.27   22.19   22.08   22.08   21.84   21.84   21.93
    18.3    18.3   17.63   18.83
                                               0   16.66   16.79       0
                                
    4429    4740 4918.05 4950.14 4950.15 4959.64 4959.64 5120.03 5120.03 5128.82
 5128.83 5140.07    5370    5757
    19.4   17.56   18.27   18.27   22.19   22.08   22.08   21.84   21.84   21.93
    18.3    18.3   17.63   18.83
                                               0   16.66   16.79       0
                                
BR Coef=-1 , 1 , 0 ,, 0 ,,,0.8,0,2,0,
WSPro=,,,, 1 ,,,, 0 ,,,, 0 ,,,,-1 ,-1 ,-1 , 0 , 0 , 0 , 0 , 0
BC Design=,, 0 ,, 0 ,,,,,,
BC HTab HWMax=24.1

Type RM Length L Ch R = 1 ,16364.84,161.82,160,170.04
XS GIS Cut Line= 5
     3202162.232    13782634.332     3202105.179    13781036.825
     3201977.935    13780509.547      3201958.88    13780289.676
      3200983.12    13777917.884
#Sta/Elev= 30
 2780.71   24.98  2895.2   23.45 2948.07   20.67 2984.93   23.17 3360.96   20.34
 3776.43   22.43 4912.26   16.33 4946.01     6.9 4966.26     3.8 4973.74   -1.14
 5002.03   -3.29 5032.89   -1.35 5040.62    4.64  5053.7     6.7    5143   16.23
 5184.41   19.33 5578.01   19.45  5662.4   17.77 5694.62    20.2 5805.67    22.3
 6112.47   23.47 6517.48   21.48 6554.76    23.4 6813.01   22.98  6847.6   20.62
 6918.08   20.63 6990.28   23.67 7462.32   22.76 7632.61   24.99 7707.01   21.91
#Mann= 3 ,-1 , 0
 2780.71     .15       0 4912.26    .032       0    5143     .15       0
#XS Ineff= 2 , 0
       0 4912.26    17.5    5143       0    17.7
Permanent Ineff=
       F       F
#Block Obstruct= 1 ,-1
 5206.48 5862.35   18.76
Bank Sta=4912.26,5143
XS Rating Curve= 0
Exp/Cntr=0.5,0.3

Type RM Length L Ch R = 1 ,16204.84,951.96,1271.97,1634.98
XS GIS Cut Line= 5
     3202322.131    13782628.622     3202264.501    13781014.983
     3202136.297    13780483.727     3202116.167    13780251.456
     3201131.088     13777857.01
#Sta/Elev= 30
 2777.37   25.42  2909.3   21.16    2971   24.35  3224.5   20.87 3392.71   24.29
 3523.43   20.99 3626.78    23.6 4112.59   19.87 4336.69   22.04 4413.37   18.61
  4509.5   20.21    4888   14.53 5002.03   -3.29 5022.14   -3.07 5032.89   -1.35
 5040.62    4.64    5141   17.83  5315.3   16.36 5528.27   20.68 5715.91   18.34
 5805.97   22.27 5982.54   20.22 6068.83   23.55 6305.98   21.48 6461.41   24.23
 6675.15   20.43 6791.01   23.08 6894.69   19.95  7043.7   24.08 7760.85   22.95
#Mann= 3 ,-1 , 0
 2777.37     .15       0    4888    .032       0    5141     .15       0
#Block Obstruct= 2 ,-1
 4683.65 4827.95   16.17 5230.77 5465.59   18.43
Bank Sta=4888,5141
XS Rating Curve= 0
Exp/Cntr=0.3,0.1