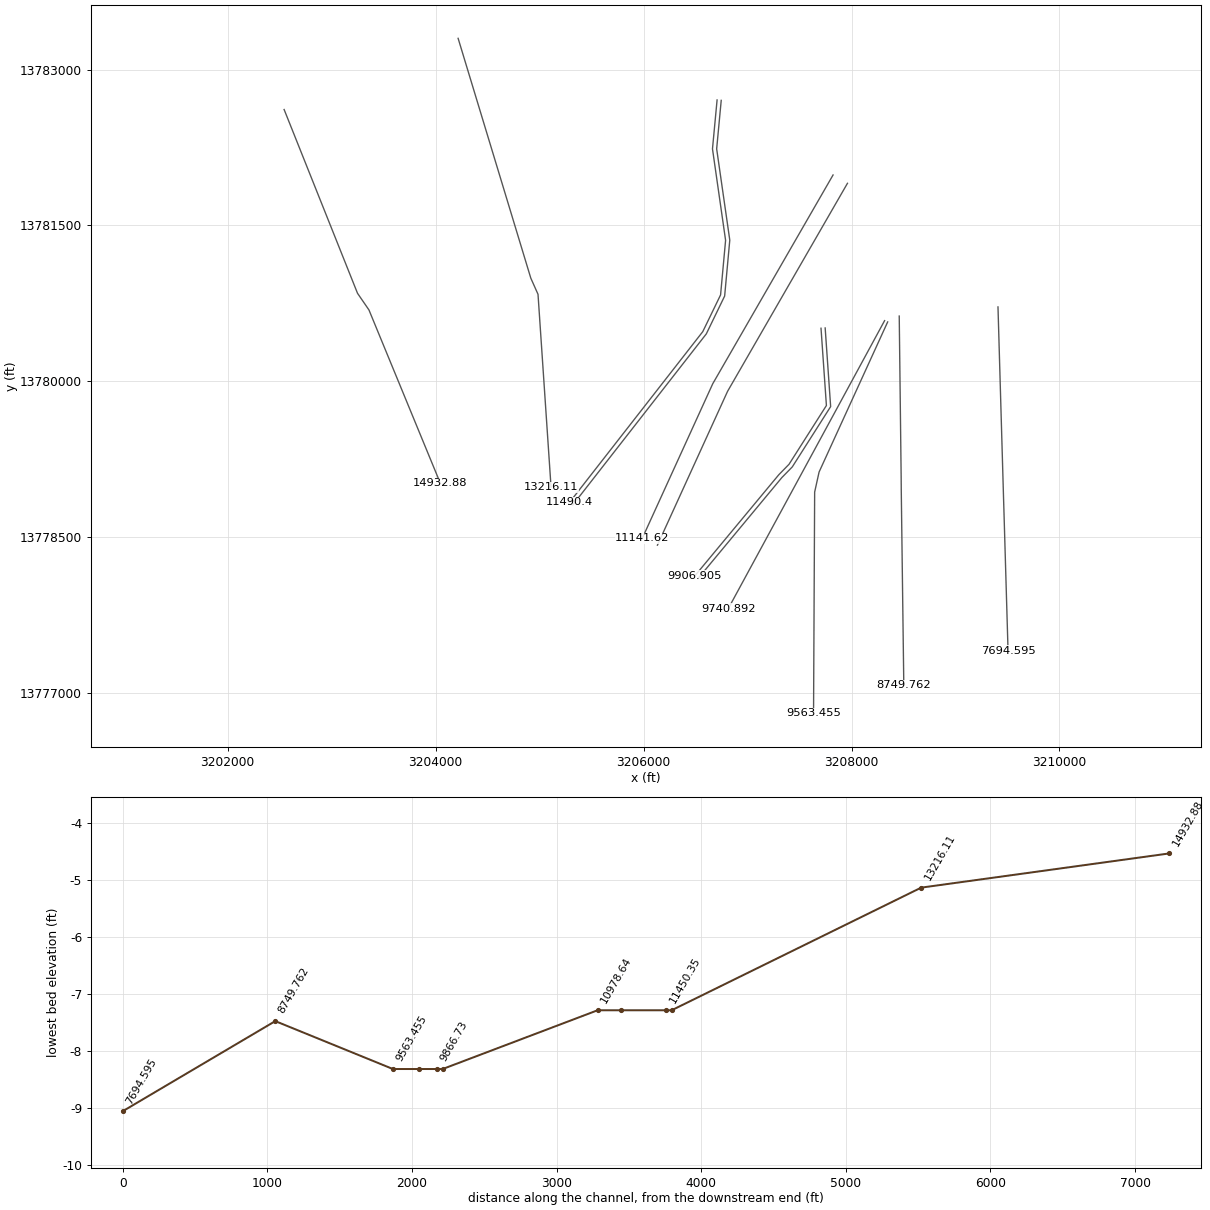
HEC-RAS study B104_00_00.prj: B104-00-00

--- B104_00_00.g01 (geometry) --- (continued)

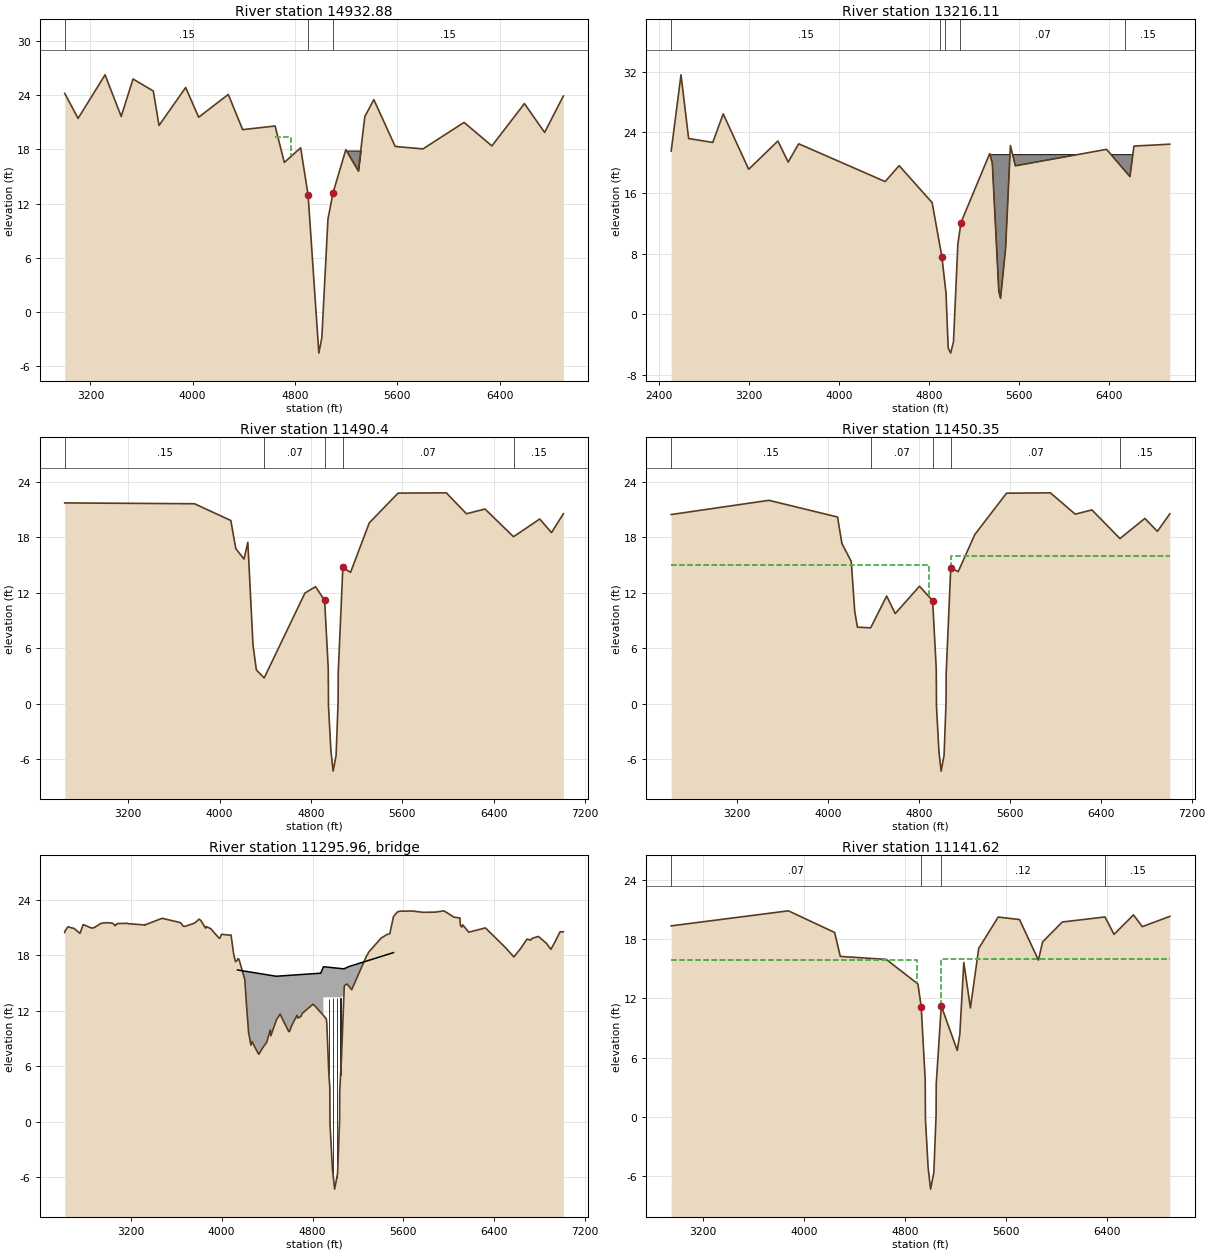
Type RM Length L Ch R = 1 ,14932.88,1767.86,1716.76,1558.19
XS GIS Cut Line= 4
     3202542.591    13782615.314     3203248.505    13780847.848
     3203358.618    13780687.524     3204045.008    13779020.924
#Sta/Elev= 30
 2999.24   24.18 3103.74   21.41 3314.82   26.23 3441.09   21.63 3533.48   25.77
 3692.21   24.44 3736.82   20.63 3945.24   24.83 4046.79   21.54 4278.57   24.06
  4390.8   20.17 4644.55   20.57 4716.89   16.54 4844.35   18.16 4902.75   12.94
 4986.88   -4.54 5010.08   -2.84 5058.14   10.28 5097.25   13.16 5197.91   17.95
 5295.35    15.6 5346.51   21.61 5417.05   23.49 5583.99   18.31 5801.37   18.04
  6122.8   20.97 6340.36   18.37 6594.71   23.05 6752.82   19.86 6899.37   23.89
#Mann= 3 ,-1 , 0
 2999.24     .15       0 4902.75    .032       0 5097.25     .15       0
#XS Ineff= 1 ,-1
 4644.91 4771.55   19.31
Permanent Ineff=
       F
#Block Obstruct= 1 ,-1
 5199.01 5318.88   17.86
Bank Sta=4902.75,5097.25
XS Rating Curve= 0
Exp/Cntr=0.3,0.1

Type RM Length L Ch R = 1 ,13216.11,2113.68,1725.71,1334.56
XS GIS Cut Line= 4
      3204216.17     13783299.96     3204915.223    13780993.597
     3204984.671     13780837.98     3205110.013    13778982.888
#Sta/Elev= 30
 2504.89   21.52  2592.2   31.57 2660.26   23.17 2874.91   22.65 2967.98   26.42
 3194.92   19.11 3455.08   22.84 3546.43   20.06 3640.26   22.47 4409.98   17.49
 4534.48   19.59 4828.22   14.71 4914.79    7.59  4952.1    2.74 4971.12   -4.46
 4993.27   -5.14 5018.46   -3.63 5057.07    9.21 5085.21   12.09  5340.4   21.17
 5363.83   19.94 5421.76    3.06 5437.28    2.09 5482.38    8.71    5525   22.24
 5569.41   19.57 6381.55   21.74 6589.51   18.14 6624.98   22.17  6944.6   22.42
#Mann= 5 ,-1 , 0
 2504.89     .15       04902.325     .07       04946.725    .032       0
5079.915     .07       06545.015     .15       0
#Block Obstruct= 2 ,-1
 4660.25  4797.8   14.98 5344.54  6944.6   21.04
Bank Sta=4914.79,5085.21
XS Rating Curve= 0
Exp/Cntr=0.3,0.1

Type RM Length L Ch R = 1 ,11490.4 ,46.61,40.06,40.02
XS GIS Cut Line= 6
     3206707.009    13782707.161     3206662.726    13782236.647
     3206788.821    13781357.312      3206740.59    13780832.139
     3206569.408    13780478.925     3205287.633    13778836.281
#Sta/Elev= 30
 2645.15   21.69 3781.26    21.6  4099.2   19.79 4142.65   16.75 4214.42   15.62
 4248.09   17.43 4293.28    6.33 4322.75    3.64  4391.1    2.78 4747.77   11.95
 4840.54   12.64 4920.32   11.16 4952.01    3.79 4954.11    -.26 4975.54   -5.16
 4994.79   -7.29 5020.67   -5.59 5038.27     .21 5039.38    3.33 5079.68   14.73
 5147.07   14.18 5310.84   19.53 5563.39   22.75 5985.24   22.78 6161.52   20.52
 6324.25   21.03 6573.54   18.04 6803.33   19.95 6905.99   18.48 7010.03   20.52
#Mann= 5 ,-1 , 0
 2645.15     .15       0  4391.1     .07       0 4920.32    .032       0
 5079.68     .07       0 6573.54     .15       0
#XS Ineff= 2 , 0
         4833.61   12.55
Permanent Ineff=
       F       F
Bank Sta=4920.32,5079.68
XS Rating Curve= 0
Exp/Cntr=0.5,0.3

Type RM Length L Ch R = 1 ,11450.35,333.57,308.72,404.83
XS GIS Cut Line= 6
     3206746.833    13782703.413     3206702.934    13782236.985
     3206829.144    13781359.003     3206779.758    13780821.239
     3206603.368    13780457.279      3205319.21    13778811.727
#Sta/Elev= 30
 2619.62   20.48 3479.59   22.02 4083.26   20.21 4122.28   17.33 4204.22    15.4
  4234.6   10.01 4258.28    8.29 4374.74    8.22 4515.61   11.66 4591.02    9.76
 4804.31   12.72 4920.32   11.16 4952.01    3.79 4954.11    -.26 4975.54   -5.16
 4994.79   -7.29 5020.67   -5.59 5038.27     .21 5039.38    3.33 5079.68   14.73
 5144.73   14.29 5291.57   18.32 5570.36   22.79 5956.75   22.83 6174.66   20.52
 6321.64   20.98 6568.64   17.88 6787.81   20.06 6897.66   18.66 7007.42   20.56
#Mann= 5 ,-1 , 0
 2619.62     .15       0 4374.74     .07       0 4920.32    .032       0
 5079.68     .07       0 6568.64     .15       0
#XS Ineff= 2 , 0
       0    4886      15 5079.68       0      16
Permanent Ineff=
       F       F
Bank Sta=4920.32,5079.68
XS Rating Curve= 0
Exp/Cntr=0.5,0.3

Type RM Length L Ch R = 3 ,11295.96,,,
BEGIN DESCRIPTION:
Bay Area Blvd
END DESCRIPTION:
Bridge Culvert--1,0,-1,-1, 0
Deck Dist Width WeirC Skew NumUp NumDn MinLoCord MaxHiCord MaxSubmerge Is_Ogee
104,113,2.6,0, 9, 9, , , 0.95, 0, 0,0,,
    4140    4480 4872.35 4896.12 4896.12 5076.76 5076.76 5118.91    5513
   16.43   15.75   16.08   16.78   16.78   16.55   16.55   16.79   18.31
                                   13.47   13.47
    4140    4480 4872.35 4896.12 4896.12 5076.76 5076.76 5118.91    5513
   16.43   15.75   16.08   16.78   16.78   16.55   16.55   16.79   18.31
                                   13.47   13.47
Pier Skew, UpSta & Num, DnSta & Num=  ,4944, 4 ,4944, 4 , 3 , 3 , 0 ,,
     1.4     1.4     2.2     2.2
      -6   11.09   11.09   13.29
     1.4     1.4     2.2     2.2
      -6   11.09   11.09   13.29
Pier Skew, UpSta & Num, DnSta & Num=  ,4980, 4 ,4980, 4 , 3 , 3 , 0 ,,
     1.4     1.4     2.2     2.2
      -6   11.23   11.23   13.43
     1.4     1.4     2.2     2.2
      -6   11.23   11.23   13.43
Pier Skew, UpSta & Num, DnSta & Num=  ,5013, 4 ,5013, 4 , 3 , 3 , 0 ,,
     1.4     1.4     2.2     2.2
      -6   11.16   11.16   13.36
     1.4     1.4     2.2     2.2
      -6   11.16   11.16   13.36
Pier Skew, UpSta & Num, DnSta & Num=  ,5047, 4 ,5047, 4 , 3 , 3 , 0 ,,
     1.4     1.4     2.2     2.2
      -6   11.24   11.24   13.44
     1.4     1.4     2.2     2.2
      -6   11.24   11.24   13.44
BR Coef=-1 , 1 , 1 ,1.25, 0 ,,,0.8,-1,2,0,
WSPro=,,,, 1 ,,,, 0 ,,,, 0 ,,,,-1 ,-1 ,-1 , 0 , 0 , 0 , 0 , 0
BR U #Sta/Elev= 134
 2619.62   20.48    2624   20.69 2647.81    21.1 2691.57   20.95 2699.12   20.95
  2753.9   20.39 2781.85   21.33 2784.34   21.33 2848.78      21 2860.99   20.96
 2884.87   21.04 2889.02   21.09 2939.39   21.48 2991.27   21.55 3040.47   21.49
 3063.75   21.23 3066.69   21.29 3069.63   21.29 3080.64   21.45 3088.11   21.45
 3172.78   21.48 3175.29   21.44 3178.49   21.44  3323.5    21.3 3324.77   21.34
  3326.1   21.31  3474.4   22.01 3475.43      22 3477.22      22 3479.59   22.02
 3535.32   21.85 3632.07   21.57 3640.39   21.53 3663.39   21.16 3678.01   21.15
 3762.44    21.5 3802.16   21.93 3812.93   21.82 3817.47   21.79 3859.28   20.95
 3863.46   21.12 3874.42   21.07 3903.87   20.91 3975.58    19.9 3984.25   19.86
  3999.6   20.29  4058.7   20.21 4083.26   20.21 4106.49   18.12 4122.28   17.33
 4135.86   17.45 4143.51   17.66 4153.55   17.56 4204.22    15.4 4205.06   15.16
 4219.14   12.65 4233.24   10.34 4233.89   10.24  4234.6   10.01 4237.21    9.69
 4258.28    8.29 4267.56    8.68 4318.31    7.48 4327.67    7.31 4329.22    7.34
 4360.83    7.99 4374.74    8.22 4397.35    8.61 4427.67    9.92 4429.71    9.86
  4433.2    9.31 4484.18   11.07 4515.61   11.66 4528.18    11.3 4591.02    9.76
 4598.48    9.79 4616.04   10.38 4663.75   11.52 4670.87   11.23 4698.06   11.39
 4709.76   11.73 4800.35   12.69 4804.31   12.72  4810.1   12.68 4886.53   11.64
 4886.54   11.64 4920.32   11.16 4925.21   10.77 4944.38    5.02 4952.01    3.79
 4954.11    -.26 4975.54   -5.16 4994.79   -7.29 5020.67   -5.59 5038.27     .21
 5039.38    3.33 5054.46    6.82 5079.68   14.73 5104.58   14.91 5144.73   14.29
 5278.49   18.03 5286.03   18.12 5291.57   18.32 5403.11   19.87 5455.59   20.27
 5480.48   20.35 5493.16   21.12 5512.55    22.2 5546.73   22.71 5570.36   22.79
 5677.06   22.81 5772.52   22.67 5881.51   22.69 5956.75   22.83 6045.73   22.14
 6097.22   22.06 6101.63   21.23 6114.87   21.07 6121.84   21.32 6174.66   20.52
 6321.64   20.98 6499.05   18.84 6568.64   17.88 6571.64   17.84  6633.9   18.79
 6687.47   19.77 6720.29   19.66 6733.82   19.86 6787.81   20.06 6858.51   19.31
 6897.66   18.66 6926.53    19.3 6978.19   20.56 7007.42   20.56
BR U #Mann= 5
 2619.62     .15 4374.74     .07 4920.32    .015 5079.68     .07 6568.64     .15
BR D #Sta/Elev= 129
 2949.54   19.33 2975.63   19.56 3005.73    19.8 3105.96   19.37 3243.65   19.87
 3278.91   19.75 3296.81   20.47 3340.28   20.02  3373.7   20.34 3393.13   20.16
 3460.24   20.58  3566.2   21.03 3716.86   20.54 3738.44   20.47 3745.89   20.36
 3878.02   20.85 3883.76   20.81 3954.07   19.78 3987.22    19.3  3988.6   19.26
 3989.62   19.25 4082.83    18.7 4112.17   18.87 4244.77   18.66 4268.14   17.08
 4289.38   16.24 4451.39   16.54 4459.02   16.64 4467.35   16.57  4477.7   16.57
 4582.41   16.09 4653.63   15.94 4662.07   15.82 4666.74   15.74 4711.56    14.4
 4713.63   14.33 4713.92   14.34 4714.21   14.33 4832.41   13.69 4871.01   13.53
 4900.34   13.51 4904.45   13.45 4913.09   13.01 4919.73   12.67 4922.31   12.53
 4924.94   11.73    4925   11.64 4930.32   11.16 4935.21   10.77 4954.38    5.02
 4962.01    3.79 4964.11    -.26 4985.54   -5.16 5004.79   -7.29 5030.67   -5.59
 5048.27     .21 5049.38    3.33 5064.46    6.82 5089.68   11.23 5114.58   10.57
 5200.41    6.68 5211.06    6.65 5216.08    6.74 5236.22    8.34 5250.71   12.79
 5261.66   14.03 5266.62    15.3 5267.95   15.62 5273.99   15.83 5287.22   14.23
 5294.39   13.35 5299.12   12.38 5312.41   11.16 5317.41   11.03 5320.26   11.03
  5330.6   12.46 5343.92   13.88 5386.07   17.05 5408.83   17.59 5448.94   18.59
 5496.31    19.6 5540.31   20.22 5557.06   20.19  5564.7   20.32 5592.42   20.34
 5686.54   19.94 5709.26   19.97 5733.21   18.88 5767.74   18.88 5801.44   17.78
 5829.55   16.67 5846.23   16.17 5859.19   15.87 5891.93    17.7 5923.08   17.72
 5946.43   18.41 5986.03   18.95 6001.47   19.15 6048.04   19.72 6082.63   19.84
 6162.15   18.92 6202.05   19.58 6243.57   19.76 6285.12   19.52 6297.08   19.83
 6352.25   19.87 6386.74   20.23 6405.47   20.42 6423.93   19.41 6438.44   18.56
 6458.33   18.47  6492.7   19.52 6513.35   19.85 6520.87   19.69 6563.15   20.08
 6566.21   20.13  6573.5   19.95 6585.15   20.31  6612.1   20.44 6634.17    19.5
 6682.32   19.25 6734.34   20.27 6735.18   20.27 6775.94   20.22 6781.85   20.26
 6792.47   20.37 6848.97   20.36 6852.14   20.38 6900.34   20.29
BR D #Mann= 4
 2949.54     .07 4930.32    .015 5089.68     .12 6386.74     .15
BC Design=,, 0 ,, 0 ,,,,,,
BC HTab HWMax=22.83

Type RM Length L Ch R = 1 ,11141.62,162.15,162.99,167.04
XS GIS Cut Line= 3
     3207822.412     13781985.53     3206665.417    13779977.988
     3205987.619    13778491.504
#Sta/Elev= 30
 2949.54   19.33 3878.02   20.85 4244.77   18.66 4289.38   16.24 4653.63   15.94
 4904.45   13.45 4930.32   11.16 4962.01    3.79 4964.11    -.26 4985.54   -5.16
 5004.79   -7.29 5030.67   -5.59 5048.27     .21 5049.38    3.33 5089.68   11.23
 5216.08    6.74 5236.22    8.34 5267.95   15.62 5320.26   11.03 5386.07   17.05
 5540.31   20.22 5709.26   19.97 5859.19   15.87 5891.93    17.7 6048.04   19.72
 6386.74   20.23 6458.33   18.47  6612.1   20.44 6682.32   19.25 6900.34   20.29
#Mann= 4 ,-1 , 0
 2949.54     .07       0 4930.32    .032       0 5089.68     .12       0
 6386.74     .15       0
#XS Ineff= 2 , 0
       0    4898    15.9 5089.68       0      16
Permanent Ineff=
       F       F
Bank Sta=4930.32,5089.68
XS Rating Curve= 0
Exp/Cntr=0.5,0.3

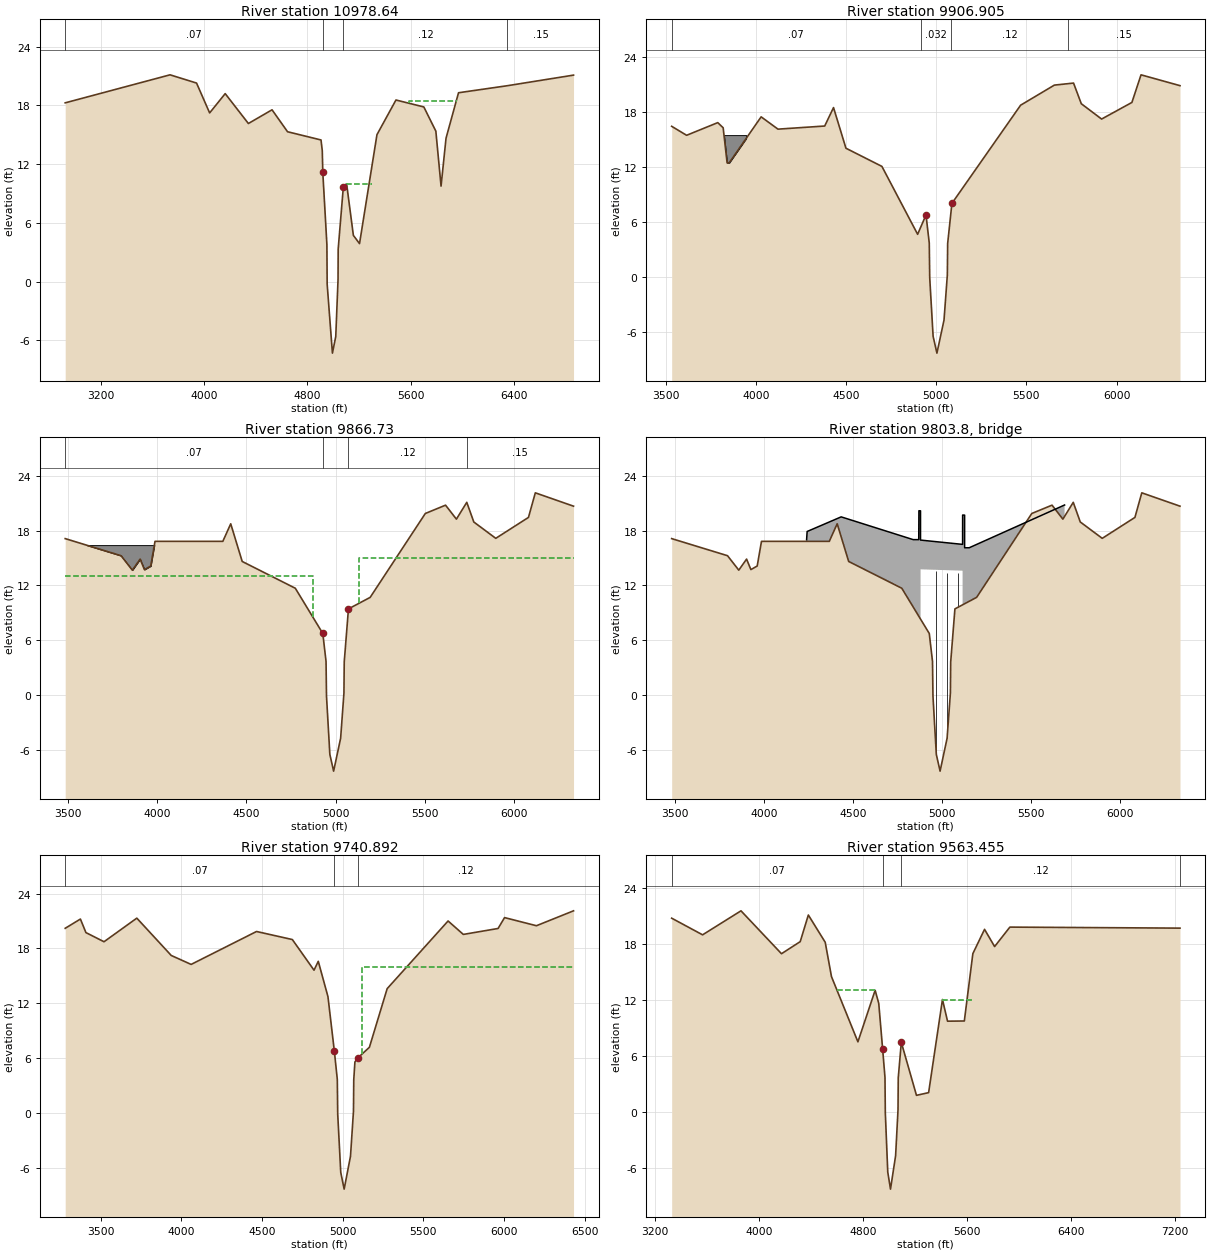
Type RM Length L Ch R = 1 ,10978.64,1030.57,1071.74,951.14
XS GIS Cut Line= 3
     3207961.038    13781905.637     3206807.841    13779904.686
     3206133.199    13778425.123
#Sta/Elev= 30
 2925.95   18.26 3737.71   21.12 3942.79   20.28  4044.2   17.23 4164.67    19.2
 4344.22   16.15 4527.35   17.55 4647.34   15.31 4906.55   14.47 4916.32   13.37
 4920.32   11.16 4952.01    3.79 4954.11    -.26 4994.79   -7.29 5020.67   -5.59
 5038.27     .21 5039.38    3.33 5079.68    9.72 5104.58      10 5157.05    4.73
 5204.67    3.89 5339.63   15.01 5486.72   18.55 5702.59   17.84  5795.6   15.37
 5835.88    9.76  5874.4   14.65 5971.13   19.29 6349.91   20.01 6861.54   21.09
#Mann= 4 ,-1 , 0
 2925.95     .07       0 4920.32    .032       0 5079.68     .12       0
 6349.91     .15       0
#XS Ineff= 2 ,-1
 5584.01 5955.69   18.49 5103.13 5299.72    9.99
Permanent Ineff=
       F       F
Bank Sta=4920.32,5079.68
XS Rating Curve= 0
Exp/Cntr=0.3,0.1

Type RM Length L Ch R = 1 ,9906.905,59.39,40.18,40.62
XS GIS Cut Line= 5
     3207706.688    13780511.537      3207758.54    13779768.318
     3207399.026    13779203.106     3207300.316    13779102.091
      3206493.33    13778130.081
#Sta/Elev= 30
 3532.47    16.4 3615.34   15.42 3788.06    16.8 3818.08   16.24 3839.87   12.42
 3852.46   12.44 4028.76   17.43 4122.07   16.09 4381.24   16.43 4430.18   18.44
 4499.12   14.01  4698.6   12.03 4896.67    4.63 4943.11    6.74 4961.21    3.68
 4963.74     -.1 4982.59   -6.49  5003.7   -8.32 5043.03   -4.72 5061.53     .21
 5063.25    3.63 5086.89       8 5467.89    18.7 5655.23   20.89 5761.49   21.11
 5804.49   18.86 5917.13   17.19 6085.16      19 6135.83   22.01 6351.93   20.83
#Mann= 4 ,-1 , 0
 3532.47     .07       04914.005    .032       05083.175     .12       0
5731.645     .15       0
#Block Obstruct= 1 ,-1
 3807.69 3945.34   15.44
Bank Sta=4943.11,5086.89
XS Rating Curve= 0
Exp/Cntr=0.5,0.3

Type RM Length L Ch R = 1 ,9866.73 ,113.75,125.84,232.35
XS GIS Cut Line= 5
     3207746.591    13780514.321      3207799.36    13779757.963
     3207430.543    13779178.127     3207330.057    13779075.294
     3206524.106     13778104.53
#Sta/Elev= 30
 3483.33   17.12 3796.63   15.25 3859.75   13.67 3903.45   14.88 3927.59   13.73
 3962.99   14.12 3987.02   16.82 4367.34   16.82 4411.66   18.74 4475.99   14.62
 4773.86   11.69 4928.11    6.74 4946.21    3.68 4948.74     -.1 4967.59   -6.49
  4988.7   -8.32 5028.03   -4.72 5046.53     .21 5048.25    3.63 5071.89    9.43
 5193.67   10.69 5503.02   19.87 5616.45   20.78 5677.33   19.25 5735.53   21.09
 5774.93   18.94 5898.14   17.15 6081.49   19.44 6119.92   22.13 6334.22   20.67
#Mann= 4 ,-1 , 0
 3483.33     .07       0 4928.11    .032       0 5071.89     .12       0
 5735.53     .15       0
#XS Ineff= 2 , 0
       0    4871      13    5130       0      15
Permanent Ineff=
       F       F
#Block Obstruct= 1 ,-1
 3297.57 4015.52   16.41
Bank Sta=4928.11,5071.89
XS Rating Curve= 0
Exp/Cntr=0.5,0.3

Type RM Length L Ch R = 3 ,9803.8  ,,,
BEGIN DESCRIPTION:
University Blvd
END DESCRIPTION:
Bridge Culvert--1,0,-1,-1, 0
Deck Dist Width WeirC Skew NumUp NumDn MinLoCord MaxHiCord MaxSubmerge Is_Ogee
56,44,2.6,0, 14, 14, , , 0.95, 0, 0,0,,
    4240    4243    4434 4837.84 4868.95 4869.96 4879.03 4879.03 5114.91  5115.1
 5126.34 5126.35 5151.94    5687
      17    17.9    19.5   17.01   17.01   20.17   20.16   16.96   16.49    19.7
   19.69   16.12   16.12    20.8
                                                           13.76   13.61
                                
    4240    4243    4434 4837.84 4868.95 4869.96 4879.03 4879.03 5114.91  5115.1
 5126.34 5126.35 5151.94    5687
      17    17.9    19.5   17.01   17.01   20.17   20.16   16.96   16.49    19.7
   19.69   16.12   16.12    20.8
                                                           13.76   13.61
                                
Pier Skew, UpSta & Num, DnSta & Num=  ,4967, 4 ,4967, 4 , 3 , 3 , 0 ,,
     1.4     1.4     2.8     2.8
     -10  11.108  11.108  13.608
     1.4     1.4     2.8     2.8
     -10  11.108  11.108  13.608
Pier Skew, UpSta & Num, DnSta & Num=  ,5028, 4 ,5028, 4 , 3 , 3 , 0 ,,
     1.4     1.4     2.8     2.8
     -10   10.88   10.88 13.3783
     1.4     1.4     2.8     2.8
     -10   10.88   10.88 13.3783
Pier Skew, UpSta & Num, DnSta & Num=  ,5088, 4 ,5088, 4 , 3 , 3 , 0 ,,
     1.4     1.4     2.8     2.8
     -10   10.84   10.84  13.344
     1.4     1.4     2.8     2.8
     -10   10.84   10.84  13.344
BR Coef=-1 , 1 , 0 ,, 0 ,,,0.8,0,2,0,
WSPro=,,,, 1 ,,,, 0 ,,,, 0 ,,,,-1 ,-1 ,-1 , 0 , 0 , 0 , 0 , 0
BC Design=,, 0 ,, 0 ,,,,,,
BC HTab HWMax=22.13

Type RM Length L Ch R = 1 ,9740.892,131.6,177.44,406.52
XS GIS Cut Line= 2
     3208318.256     13780584.68     3206814.336      13777814.3
#Sta/Elev= 30
 3278.86    20.2 3373.19   21.21 3407.33   19.73 3519.59   18.73 3722.93   21.31
 3936.43   17.23 4059.79   16.25 4465.34   19.85  4687.4   18.97 4821.88   15.62
 4848.22   16.59  4908.2   12.73 4948.11    6.74 4966.21    3.68 4968.74     -.1
 4987.59   -6.49  5008.7   -8.32 5048.03   -4.72 5066.53     .21 5068.25    3.63
  5075.4    5.58 5091.89       6  5165.3    7.19 5275.41    13.6 5653.21      21
 5747.79   19.53  5963.3   20.18 6003.37   21.37 6201.17   20.48 6431.13   22.11
#Mann= 3 ,-1 , 0
 3278.86     .07       0 4948.11    .032       0 5091.89     .12       0
#XS Ineff= 2 , 0
       0                    5120       0      16
Permanent Ineff=
       F       F
Bank Sta=4948.11,5091.89
XS Rating Curve= 0
Exp/Cntr=0.5,0.3

Type RM Length L Ch R = 1 ,9563.455,607.84,813.69,863.17
XS GIS Cut Line= 4
      3208347.75     13780572.12     3207688.093    13779128.577
     3207645.451     13778935.84     3207634.791    13776807.197
#Sta/Elev= 30
 3329.07    20.8 3567.08   19.01 3862.69   21.59  4174.5   16.98 4318.69   18.28
  4381.2   21.14 4511.08   18.21 4559.34   14.52 4762.75    7.51 4895.35   13.05
 4923.16   11.65 4953.11    6.74 4971.21    3.68 4973.74     -.1 4992.59   -6.49
  5013.7   -8.32 5053.03   -4.72 5071.53     .21 5073.25    3.63 5096.89    7.45
 5213.62    1.76 5307.09    2.05  5413.7   12.06 5452.66    9.73 5582.04    9.75
 5647.66   16.99 5737.66    19.6 5815.13   17.75 5932.67   19.84 7242.26   19.73
#Mann= 4 ,-1 , 0
 3329.07     .07       0 4953.11    .032       0 5096.89     .12       0
 7242.26     .07       0
#XS Ineff= 3 ,-1
 4598.97 4895.76   13.08 5413.15 5645.22   12.01 5097.17 5383.17    7.43
Permanent Ineff=
       F       F       F
Bank Sta=4953.11,5096.89
XS Rating Curve= 0
Exp/Cntr=0.3,0.1

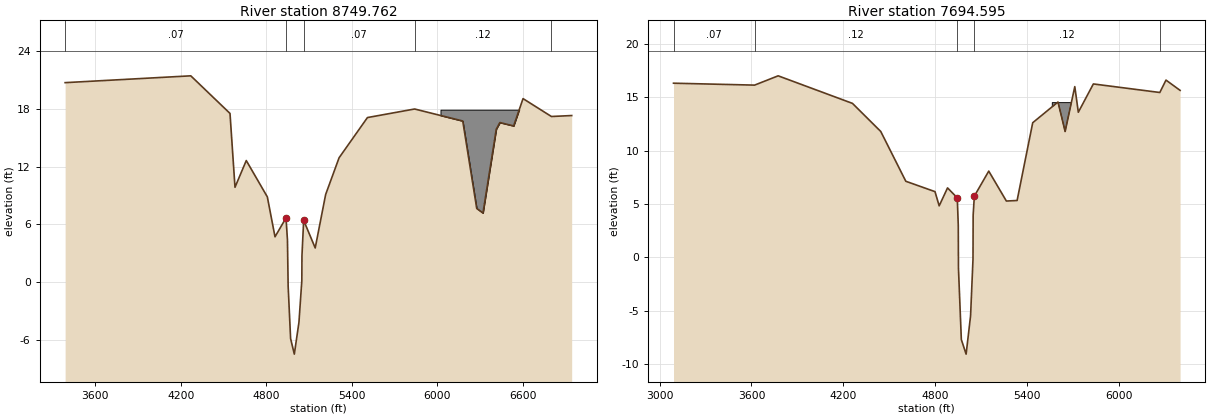
Type RM Length L Ch R = 1 ,8749.762,1040.03,1055.17,1038.35
XS GIS Cut Line= 4
     3208458.974    13780628.654     3208477.488    13779080.431
     3208478.474     13778956.59     3208502.948    13777075.532
#Sta/Elev= 30
 3388.54   20.75 4270.09   21.46 4545.19   17.55 4580.17    9.87 4659.29   12.65
 4807.08    8.87 4860.82    4.72 4938.08    6.68 4948.18    4.39 4953.02    -.39
 4970.21   -5.86 4996.33   -7.48 5028.72   -4.18 5048.97     .16 5049.87    2.74
 5061.92    6.43 5142.87    3.56  5216.1    9.12 5310.41   12.94 5509.29   17.12
 5840.38   18.01 6177.79   16.76 6275.81    7.67 6319.67    7.19 6413.05   15.91
 6438.27    16.6 6534.88   16.25 6600.75   19.09  6799.8   17.23 6941.94   17.33
#Mann= 5 ,-1 , 0
 3388.54     .07       0 4938.08    .032       0 5061.92     .07       0
 5840.38     .12       0  6799.8     .07       0
#Block Obstruct= 1 ,-1
 6021.62  6622.3   17.94
Bank Sta=4938.08,5061.92
XS Rating Curve= 0
Exp/Cntr=0.3,0.1

Type RM Length L Ch R = 1 ,7694.595,755.13,767.7,368.85
XS GIS Cut Line= 4
     3209408.818    13780716.602     3209462.655    13778865.193
     3209466.097     13778753.73     3209505.562    13777409.736
#Sta/Elev= 30
 3091.12    16.3 3620.45   16.12 3774.56   16.99 4259.76   14.41 4444.59   11.78
  4608.2    7.12 4798.74    6.15 4826.11    4.82 4880.67     6.5 4944.24    5.57
 4950.77       3 4952.02   -1.03 4970.83    -7.7 5002.02   -9.06 5031.18   -5.46
 5046.96    -.16 5047.94    3.96 5055.76    5.73 5149.83    8.07 5264.94    5.27
 5335.02    5.32 5436.95    12.6 5602.02   14.54  5648.7   11.78 5711.77   15.98
 5734.78   13.58 5832.98   16.23 6267.07   15.43 6307.32   16.59  6399.4   15.63
#Mann= 5 ,-1 , 0
 3091.12     .07       0 3620.45     .12       0 4944.24    .032       0
 5055.76     .12       0 6267.07     .07       0
#Block Obstruct= 1 ,-1
 5564.78 5701.75   14.48
Bank Sta=4944.24,5055.76
XS Rating Curve= 0
Exp/Cntr=0.3,0.1