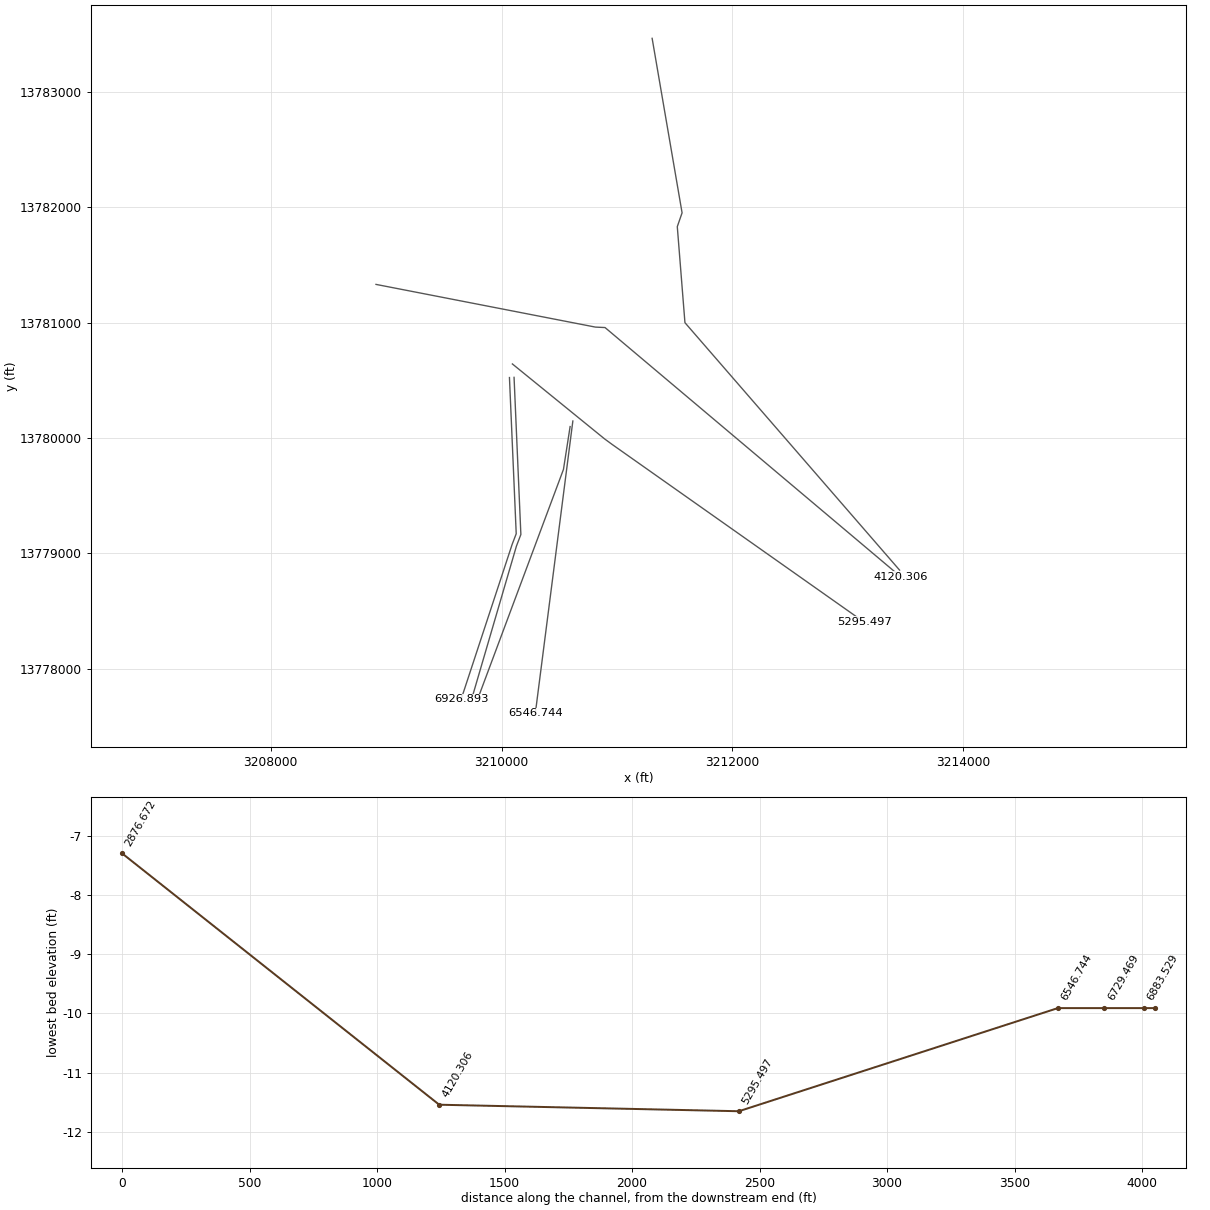
HEC-RAS study B104_00_00.prj: B104-00-00

--- B104_00_00.g01 (geometry) --- (continued)

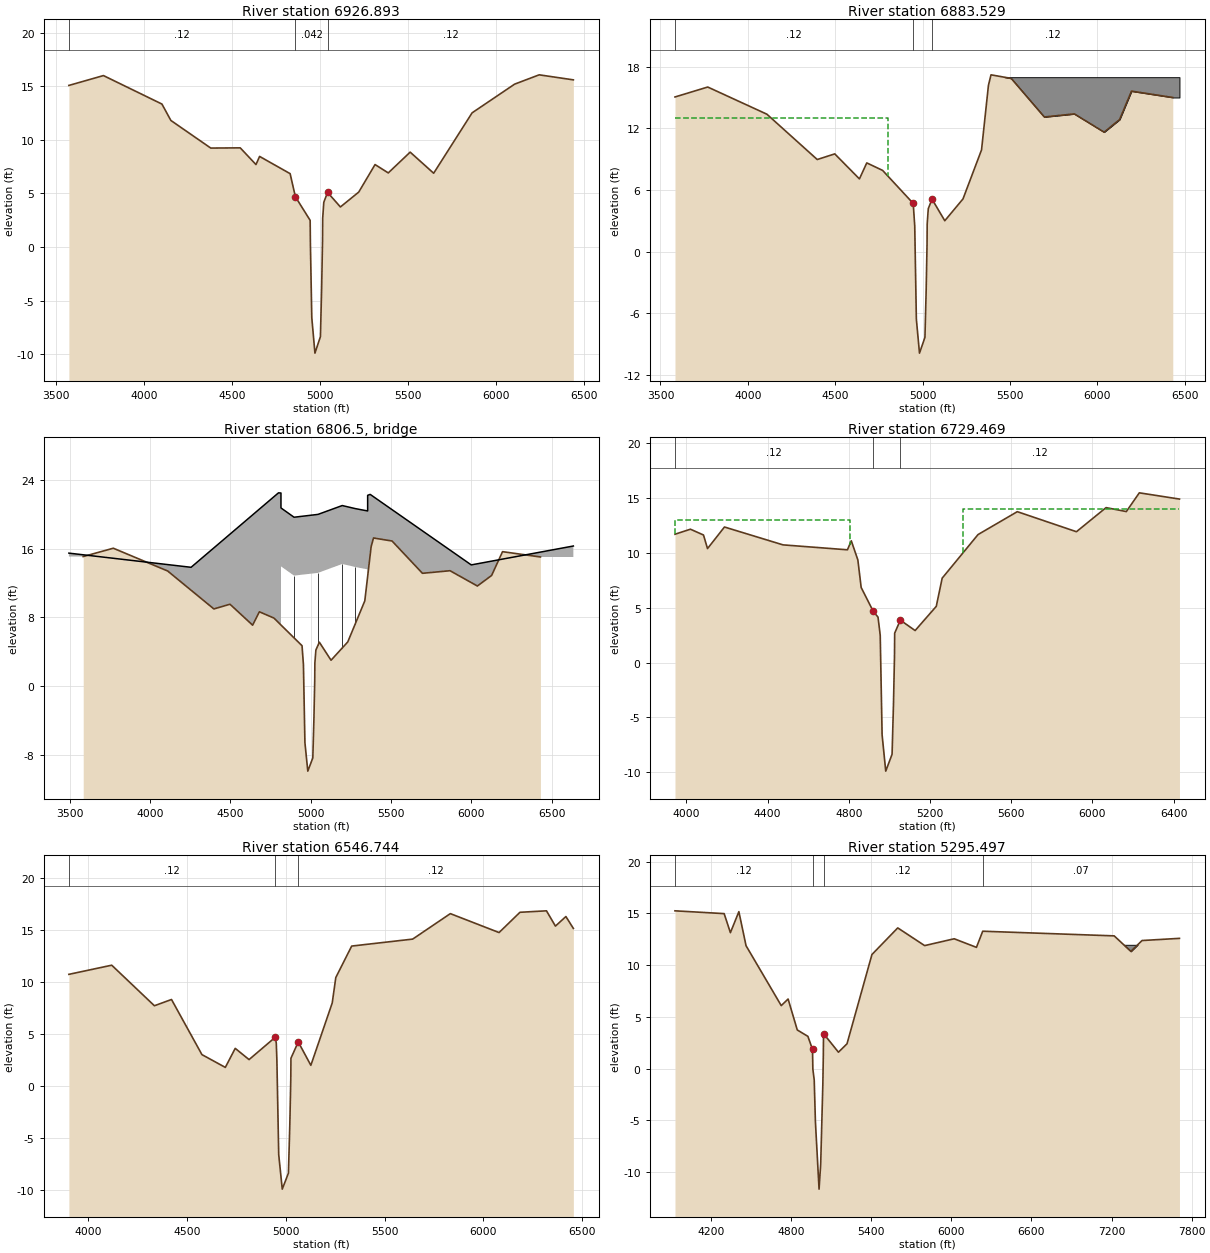
Type RM Length L Ch R = 1 ,6926.893,40.04,43.36,70.28
XS GIS Cut Line= 4
     3210068.692    13780523.495     3210127.311    13779170.295
       3210092.1    13779078.285     3209649.766    13777735.199
#Sta/Elev= 30
 3573.65   15.09 3770.01   16.01 4102.47   13.35 4153.23   11.82 4379.94    9.24
 4547.46    9.26 4636.91     7.7 4657.45    8.46    4831    6.85    4861    4.69
 4944.81    2.49 4946.26     .29 4954.08   -6.59 4972.03   -9.91 5003.21   -8.37
 5010.15    -3.8 5015.17     .62 5016.04    2.68 5022.35    4.18 5043.89     5.1
 5116.78    3.74 5220.97    5.13 5313.67     7.7 5388.74    6.92 5513.23    8.86
 5646.76    6.89 5865.23   12.53  6106.9   15.21 6246.48   16.08 6440.69   15.61
#Mann= 3 ,-1 , 0
 3573.65     .12       0    4861    .042       0 5043.89     .12       0
Bank Sta=4861,5043.89
XS Rating Curve= 0
Exp/Cntr=0.5,0.3

Type RM Length L Ch R = 1 ,6883.529,979.21,154.06,121.29
XS GIS Cut Line= 4
     3210108.655    13780525.226     3210167.633    13779163.743
      3210129.11    13779063.078     3209742.319    13777741.369
#Sta/Elev= 30
 3583.28   15.07 3770.57   16.04 4109.04   13.39 4397.06    8.97 4497.34    9.52
 4638.36    7.08 4680.41    8.64 4771.03    7.91 4946.11    4.69 4954.81    2.49
 4964.08   -6.59 4982.03   -9.91 5013.21   -8.37 5020.15    -3.8 5025.17     .62
 5026.04    2.68 5032.35    4.18 5053.89     5.1 5126.78       3 5230.97    5.13
    5337    9.91 5376.51   16.21 5391.18   17.23 5506.85   16.88 5695.97   13.12
 5867.89   13.42 6038.26   11.64 6127.04   12.87 6194.89   15.64 6430.97   15.02
#Mann= 3 ,-1 , 0
 3583.28     .12       0 4946.11    .042       0 5053.89     .12       0
#XS Ineff= 2 , 0
       0    4800      13    5365       0      14
Permanent Ineff=
       F       F
#Block Obstruct= 2 ,-1
 5438.57 6469.28      17 5506.83 5547.78   13.73
Bank Sta=4946.11,5053.89
XS Rating Curve= 0
Exp/Cntr=0.5,0.3

Type RM Length L Ch R = 3 ,6806.5  ,,,
BEGIN DESCRIPTION:
Middlebrook Drive
END DESCRIPTION:
Bridge Culvert--1,0,-1,-1, 0
Deck Dist Width WeirC Skew NumUp NumDn MinLoCord MaxHiCord MaxSubmerge Is_Ogee
60,65,2.6,0, 14, 14, , , 0.95, 0, 0,0,,
    3494    4255 4799.46 4814.96    4815 4896.38 5045.49 5196.48 5276.19 5354.67
 5354.79 5370.42    6000    6636
   15.47   13.82   22.49   22.47   20.73   19.65   19.98   21.01   20.66   20.38
    22.2   22.31    14.1    16.3
                       0       0   13.93   12.85   13.17   14.21   13.86   13.58
       0       0
    3494    4255 4799.46 4814.96    4815 4896.38 5045.49 5196.48 5276.19 5354.67
 5354.79 5370.42    6000    6636
   15.47   13.82   22.49   22.47   20.73   19.65   19.98   21.01   20.66   20.38
    22.2   22.31    14.1    16.3
                       0       0   13.93   12.85   13.17   14.21   13.86   13.58
       0       0
Pier Skew, UpSta & Num, DnSta & Num=  ,4896.381, 4 ,4896.381, 4 , 3 , 3 , 0 ,,
     1.5     1.5       3       3
     -10    9.85    9.85   12.85
     1.5     1.5       3       3
     -10    9.85    9.85   12.85
Pier Skew, UpSta & Num, DnSta & Num=  ,5045.486, 4 ,5045.486, 4 , 3 , 3 , 0 ,,
     1.5     1.5       3       3
     -10   10.17   10.17   13.17
     1.5     1.5       3       3
     -10   10.17   10.17   13.17
Pier Skew, UpSta & Num, DnSta & Num=  ,5196.476, 4 ,5196.476, 4 , 3 , 3 , 0 ,,
     1.5     1.5       3       3
     -10   11.21   11.21 14.2111
     1.5     1.5       3       3
     -10   11.21   11.21 14.2111
Pier Skew, UpSta & Num, DnSta & Num=  ,5276.187, 4 ,5276.187, 4 , 3 , 3 , 0 ,,
     1.5     1.5       3       3
     -10   10.86   10.86   13.86
     1.5     1.5       3       3
     -10    9.85    9.85   12.85
BR Coef=-1 , 1 , 1 ,1.25, 0 ,,,0.8,0,2,0,
WSPro=,,,, 1 ,,,, 0 ,,,, 0 ,,,,-1 ,-1 ,-1 , 0 , 0 , 0 , 0 , 0
BC Design=,, 0 ,, 0 ,,,,,,
BC HTab HWMax=17.41

Type RM Length L Ch R = 1 ,6729.469,661.43,182.72,466.68
BEGIN DESCRIPTION:
500 year flow not contained due to xsec orientation dictated by downstream xsec
END DESCRIPTION:
XS GIS Cut Line= 3
     3210594.248    13780098.852     3210536.659    13779727.827
     3209798.684    13777751.555
#Sta/Elev= 30
 3943.86   11.71 4019.77   12.17 4084.28   11.64 4104.06    10.4 4187.56   12.37
 4475.95   10.74 4793.35   10.29 4812.31   11.11  4844.6    9.37    4861    6.85
    4920    4.69    4944    4.14 4954.81    2.49 4964.08   -6.59 4982.03   -9.91
 5013.21   -8.37 5020.15    -3.8 5025.17     .62 5026.04    2.68 5053.89    3.87
 5126.78    2.92 5230.97    5.13    5260     7.7 5436.65   11.68 5630.14   13.77
 5921.43   11.94 6067.28   14.14 6167.13   13.78 6231.18   15.49 6428.89   14.92
#Mann= 3 ,-1 , 0
 3943.86     .12       0    4920    .042       0 5053.89     .12       0
#XS Ineff= 2 , 0
       0    4804      13    5361       0      14
Permanent Ineff=
       F       F
#Block Obstruct= 2 , 0
         4190.76   12.35
Bank Sta=4920,5053.89
XS Rating Curve= 0
Exp/Cntr=0.5,0.3

Type RM Length L Ch R = 1 ,6546.744,661.43,1251.25,1791.89
BEGIN DESCRIPTION:
500 year flow not contained due to xsec orientation dictated by downstream xsec
END DESCRIPTION:
XS GIS Cut Line= 2
     3210617.962    13780146.847     3210292.752    13777613.966
#Sta/Elev= 30
 3901.92   10.75 4118.76   11.63 4334.78    7.73 4421.42    8.33 4575.37    3.03
 4693.81     1.8 4743.94    3.63    4814    2.55 4946.11    4.69 4951.79    4.14
 4954.81    2.49 4964.08   -6.59 4982.03   -9.91 5013.21   -8.37 5020.15    -3.8
 5025.17     .62 5026.04    2.68    5063    4.25 5126.78       2    5235       8
 5252.99   10.44 5333.44   13.47 5642.21   14.14 5832.86   16.59 6079.52   14.77
 6185.34   16.72 6319.48   16.86 6364.85   15.39 6417.78   16.31 6455.59   15.17
#Mann= 3 ,-1 , 0
 3901.92     .12       0 4946.11    .042       0    5063     .12       0
#Block Obstruct= 2 , 0
         4074.79   11.76
Bank Sta=4946.11,5063
XS Rating Curve= 0
Exp/Cntr=0.3,0.1

Type RM Length L Ch R = 1 ,5295.497,661.43,1175.19,759.96
XS GIS Cut Line= 4
     3210094.021    13780641.364     3210893.759    13779991.384
     3210960.238     13779942.71     3213140.652    13778405.197
#Sta/Elev= 30
  3928.1   15.24 4296.52   14.97 4343.46   13.13 4406.87   15.16 4460.67   11.87
 4724.59    6.08 4775.82    6.72 4844.58    3.73 4924.21    3.11  4958.8    1.85
 4961.37    -.06 4971.54    -1.1 4980.54   -5.13  5007.9  -11.65  5020.1   -9.22
 5036.19   -1.52 5039.81    1.24  5041.2    3.38 5153.18    1.58 5217.23    2.39
 5404.31   11.02 5597.56   13.59 5799.25   11.88  6020.8   12.54 6187.54   11.71
 6234.47   13.27 7219.74   12.82 7345.08   11.32 7428.66   12.37 7709.04   12.58
#Mann= 4 ,-1 , 0
  3928.1     .12       0  4958.8    .042       0  5041.2     .12       0
 6234.47     .07       0
#Block Obstruct= 1 ,-1
 7230.77  7433.2   11.96
Bank Sta=4958.8,5041.2
XS Rating Curve= 0
Exp/Cntr=0.3,0.1

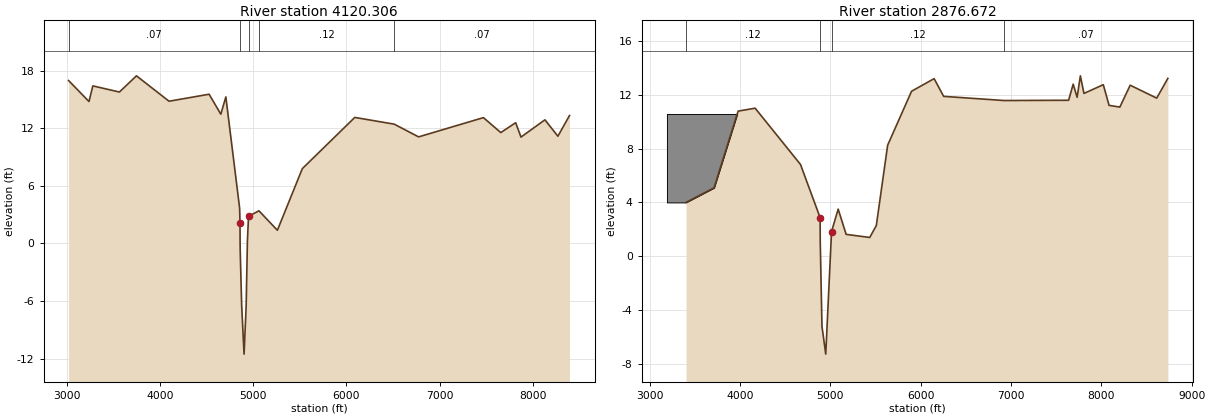
Type RM Length L Ch R = 1 ,4120.306,1877.73,1243.63,1251.16
XS GIS Cut Line= 4
     3208912.437    13781330.601     3210813.745    13780960.565
     3210896.796    13780956.716     3213460.433     13778796.04
#Sta/Elev= 30
 3020.11      17 3238.89   14.81 3280.16   16.44 3565.19    15.8 3748.03   17.49
 4097.56   14.84  4527.3   15.57 4653.05   13.49 4706.93   15.29 4854.74    3.68
 4858.43    2.17 4860.22    -.47 4876.45   -6.45 4902.33  -11.54  4924.7   -6.54
 4938.02     .22    4950    2.83 5061.79    3.41  5259.7    1.38 5527.28    7.81
 6089.77   13.15 6512.46   12.45 6774.41   11.12 7469.46   13.13 7655.93   11.57
  7815.4    12.6 7872.57    11.1  8129.2    12.9 8268.25   11.19 8392.96   13.35
#Mann= 5 ,-1 , 0
 3020.11     .07       0 4858.43     .12       0    4950    .042       0
 5061.79     .12       0 6512.46     .07       0
Bank Sta=4858.43,4950
XS Rating Curve= 0
Exp/Cntr=0.3,0.1

Type RM Length L Ch R = 1 ,2876.672,2550.34,2876.67,2548.24
XS GIS Cut Line= 5
     3211304.872    13783462.474     3211564.338    13781950.581
     3211522.822    13781830.943     3211589.122    13780998.976
     3213448.589    13778855.259
#Sta/Elev= 30
 3402.75       4 3712.92    5.09 3979.15    10.8 4167.49   11.02 4669.44    6.83
 4886.68    2.87 4888.24    1.09 4907.33   -5.23 4949.16    -7.3 5013.32    1.83
 5086.59     3.5 5174.92    1.62 5436.15    1.39 5508.96    2.28 5634.19    8.26
 5898.87   12.28 6148.58   13.22 6254.46    11.9 6922.56   11.59  7637.5   11.61
 7687.83   12.81 7731.42   11.83 7767.43   13.43 7807.14   12.12 8021.29   12.77
 8085.13   11.23 8204.42    11.1 8318.96   12.73 8612.32   11.77 8735.79   13.24
#Mann= 4 ,-1 , 0
 3402.75     .12       0 4886.68    .042       0 5013.32     .12       0
 6922.56     .07       0
#Block Obstruct= 1 ,-1
 3191.13 4037.54   10.59
Bank Sta=4886.68,5013.32
XS Rating Curve= 0
Exp/Cntr=0.3,0.1

Chan Stop Cuts=-1

--- B104_00_00.g02 (geometry) ---

Geom Title=B104-00-00 June 2007 (Floodway)
Program Version=3.11

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
River Reach=B104-00-00      ,B104-00-00_0029